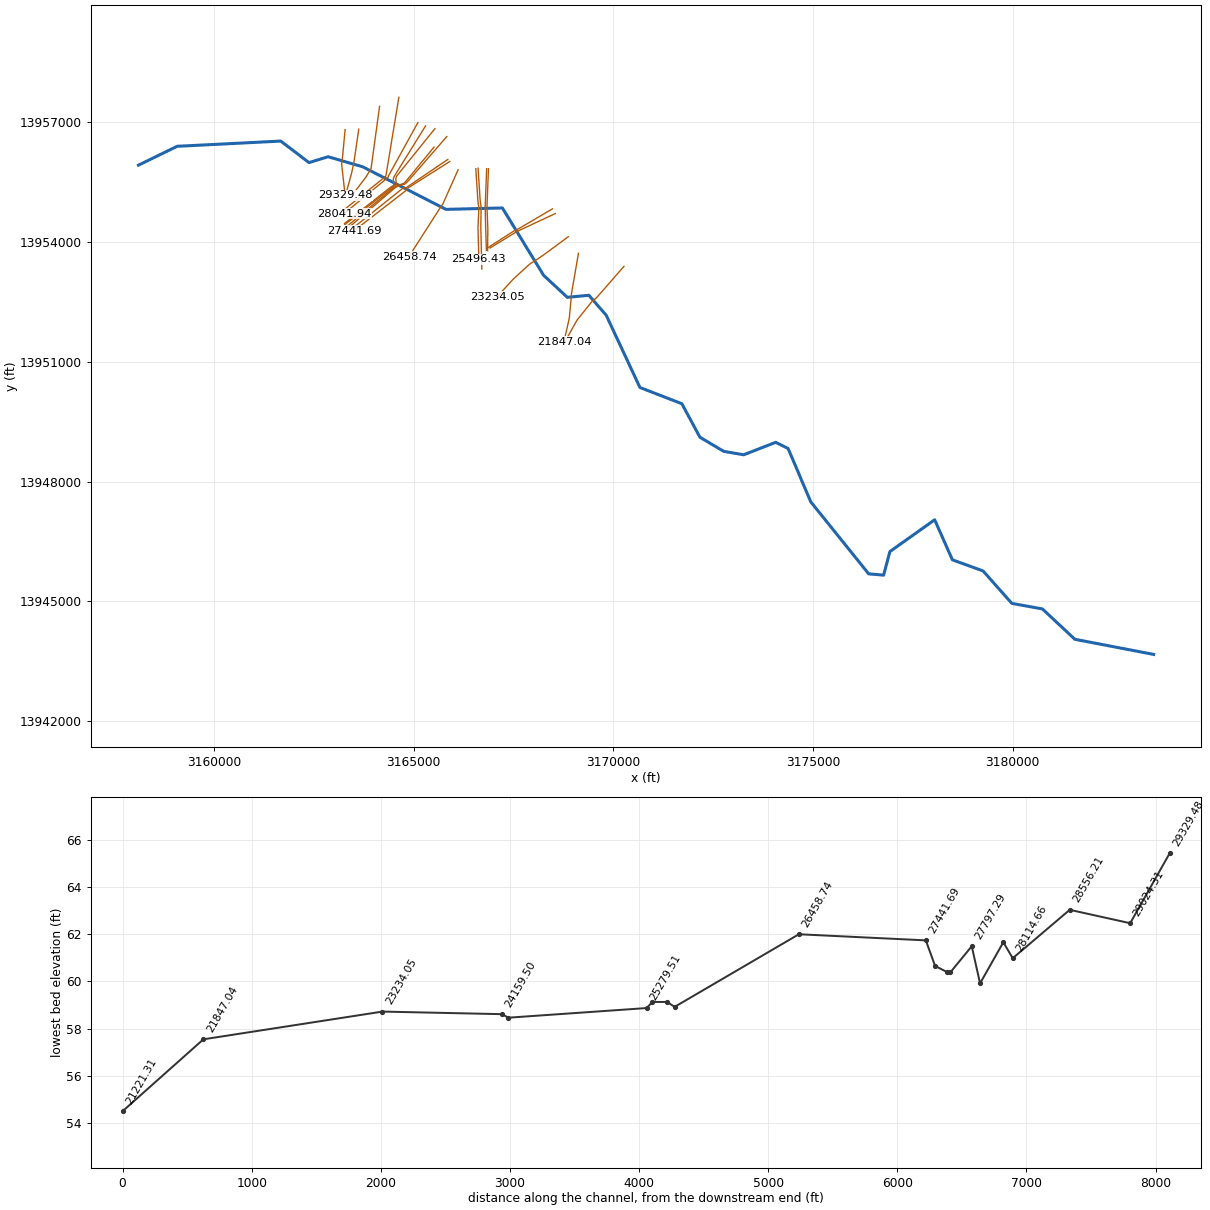
--- G103-33-00.prj (project) ---

Proj Title=G103-33-00
Current Plan=p05
Default Exp/Contr=.3,.1
English Units
Geom File=g02
Flow File=f02
Flow File=f03
Plan File=p06
Plan File=p05
Y Axis Title=Elevation
X Axis Title(PF)=Main Channel Distance
X Axis Title(XS)=Station
BEGIN DESCRIPTION:
San Jacinto River Watershed
Bens Branch
HCFCD unit G 103-33-00
(Flood Hazard Model)
10, 2, 1, 0.2% Event
Filename  G1033300.prj
Prepared by:  FTN Associates Ltd.   DATE:  May 2003
Reviewed by: 	 DATE:
STATUS (FINAL)
425BensBranch, LIDAR, Survey, bridges
Channel Slope: The low point elevations at river stations 4371.619 and 6455.492 were used to calculate the channel slope of 0.00187 ft/ft.
Extended channel and added three new xsecs upstream on 10/31/02.
END DESCRIPTION:
DSS Export Rating Curves= 0
DSS Export Rating Curve Sorted= 0
DSS Export Volume Flow Curves= 0
DXF OffsetX= 0
DXF OffsetY= 0
DXF ScaleX= 1
DXF ScaleY= 10

--- G103-33-00.p05 (plan) ---

Plan Title=Floodway
Version=Version 3.0.1  Mar 2001
Short Identifier=Floodway0607
Geom File=g02
Flow File=f03
Subcritical Flow
K Sum by GR= 0
Std Step Tol= 0.01
Critical Tol= 0.01
Num of Std Step Trials= 20
Max Error Tol= 0.3
Flow Tol Ratio= 0.001
Split Flow NTrial= 30
Split Flow Tol= 0.02
Split Flow Ratio= 0.02
Log Output Level= 0
Friction Slope Method= 1
Unsteady Friction Slope Method= 2
Parabolic Critical Depth
Global Vel Dist= 0 , 0 , 0
Global Log Level= 0
CheckData=True
Encroach Param=-1 ,0,0, 2
Encroach River=G103-33-00
Encroach Reach=G103-33-00_0032
Encroach Node=29329.48
       1  596.25  846.55
Encroach Node=29024.31
       1  638.66  897.95
Encroach Node=28556.21
       1  851.86 1151.91
Encroach Node=28114.66
       1  910.96 1373.65
Encroach Node=28041.94
       1     980 1419.12
Encroach Node=27951.87
       1     980 1419.12
Encroach Node=27861.80
       1     980 1419.12
Encroach Node=27797.29
       1    1030 1462.63
Encroach Node=27632.55
       1 1122.61    1550
Encroach Node=27608.98
       1    1150 1565.03
Encroach Node=27561.33
       1    1150 1565.03
Encroach Node=27513.68
       1    1195 1565.03
Encroach Node=27441.69
       1    1200    1550
Encroach Node=26458.74
       1  933.17 1331.41
Encroach Node=25496.43
       1     840     950
Encroach Node=25438.45
       1     850   943.3
Encroach Node=25381.46
       1   840.1     945
Encroach Node=25324.46
       1   840.1   936.5
Encroach Node=25279.51
       1     845     975
Encroach Node=24209.16
       1  925.84 1326.69
Encroach Node=24159.50
       1     936 1330.93
Encroach Node=23234.05
       1  935.01 1183.77
Encroach Node=21847.04
       1  779.02    1125
Encroach Node=21221.31
       1     800    1160
Encroach Node=19548.24
       1    1050    1250
Encroach Node=19504.82
       1    1160    1300
Encroach Node=19468.8
       1    1180    1278
Encroach Node=19432.78
       1    1181    1278
Encroach Node=19362.84
       1    1180    1300
Encroach Node=18617.86
       1 1200.33 1408.69
Encroach Node=17483.99
       1    1105    1405
Encroach Node=16519.62
       1    1350    1850
Encroach Node=16354.02
       1    1325    1850
Encroach Node=15455.73
       1    1440    2225
Encroach Node=14299.67
       1    1455    2155
Encroach Node=13295.80
       1    4060    4480
Encroach Node=13249.98
       1    4895    5310
Encroach Node=13136.92
       1    4882    4987
Encroach Node=13023.86
       1    4850    5250
Encroach Node=12941.61
       1    1570    1950
Encroach Node=11521.57
       1    1320    1531
Encroach Node=9501.098
       1    2210    2420
Encroach Node=9031.736
       1 2153.51 2348.19
Encroach Node=8367.096
       1 1602.86 1833.22
Encroach Node=8207.768
       1  1533.6 1785.71
Encroach Node=8075.989
       1 1522.75 1785.71
Encroach Node=7944.210
       1 1522.75 1773.72
Encroach Node=7739.881
       1 1347.32 1541.19
Encroach Node=6455.492
       1    1800    2075
Encroach Node=4371.619
       1    2290    2440
Encroach Node=3175.311
       1  2403.6 2604.03
Computation Interval=1HOUR
Output Interval=1HOUR
Run HTab= 0
Run UNet= 0
Run PostProcess= 0
UNET Theta= 1
UNET ZTol= 0.02
UNET ZSATol= 0.1
UNET MxIter= 20
UNET MaxInSteps= 20
UNET DtIC= 0
UNET DtMin= 0
UNET MaxCRTS= 20
UNET WFStab= 2
UNET SFStab= 1
UNET WFX= 1
UNET SFX= 1
UNET Convert EG Bridges=-1
UNET Use Existing IB Tables=-1
Instantaneous Interval=1HOUR
Write IC File= 0
Write Velocity= 0
Write Detailed= 0

--- G103-33-00.p06 (plan) ---

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Plan Title=FEMA Effective June 2007
Short Identifier=FEMAeff0607
Geom File=g02
Flow File=f02
Encroach Param=-1 ,0,0, 0
DSS File=dss

--- G103-33-00.f03 (steady flow) ---

Flow Title=Floodway
Version=Version 3.0.1  Mar 2001
Number of Profiles= 2
Profile Names=1PCT_100yr, 1PCTFloodway_100yrFW
River Rch & RM=G103-33-00,G103-33-00_0032     ,29329.48
    2193    2193
River Rch & RM=G103-33-00,G103-33-00_0032     ,28556.21
    2282    2282
River Rch & RM=G103-33-00,G103-33-00_0032     ,27441.69
    2363    2363
River Rch & RM=G103-33-00,G103-33-00_0032     ,26458.74
    2451    2451
River Rch & RM=G103-33-00,G103-33-00_0032     ,25438.45
    2565    2565
River Rch & RM=G103-33-00,G103-33-00_0032     ,24159.50
    2651    2651
River Rch & RM=G103-33-00,G103-33-00_0032     ,23234.05
    2786    2786
River Rch & RM=G103-33-00,G103-33-00_0032     ,21847.04
    2849    2849
River Rch & RM=G103-33-00,G103-33-00_0032     ,21221.31
    2983    2983
River Rch & RM=G103-33-00,G103-33-00_0032     ,13295.80
    3432    3432
River Rch & RM=G103-33-00,G103-33-00_0032     ,11521.57
    3546    3546
River Rch & RM=G103-33-00,G103-33-00_0032     ,9501.098
    3692    3692
River Rch & RM=G103-33-00,G103-33-00_0032     ,7944.210
    3837    3837
River Rch & RM=G103-33-00,G103-33-00_0032     ,6455.492
    5454    5454
Boundary for River Rch & Prof#=G103-33-00,G103-33-00_0032     , 1
Up Type= 0
Dn Type= 3
Dn Slope=.00187
Boundary for River Rch & Prof#=G103-33-00,G103-33-00_0032     , 2
Up Type= 0
Dn Type= 3
Dn Slope=.00187
DSS Import GetInterval= 0
DSS Import GetPeak= 0
DSS Import FillOption= 0

--- G103-33-00.f02 (steady flow) ---

Flow Title=FEMA Effective June 2007
Version=Version 3.0.1  Mar 2001
Number of Profiles= 4
Profile Names=10PCT_10yr, 2PCT_50yr, 1PCT_100yr, 0.2PCT_500yr
River Rch & RM=G103-33-00,G103-33-00_0032     ,29329.48
    1068    1819    2193    3396
River Rch & RM=G103-33-00,G103-33-00_0032     ,28556.21
    1109    1892    2282    3519
River Rch & RM=G103-33-00,G103-33-00_0032     ,27441.69
    1147    1960    2363    3631
River Rch & RM=G103-33-00,G103-33-00_0032     ,26458.74
    1188    2032    2451    3751
River Rch & RM=G103-33-00,G103-33-00_0032     ,25438.45
    1241    2127    2565    3906
River Rch & RM=G103-33-00,G103-33-00_0032     ,24159.50
    1280    2198    2651    4023
River Rch & RM=G103-33-00,G103-33-00_0032     ,23234.05
    1342    2310    2786    4205
River Rch & RM=G103-33-00,G103-33-00_0032     ,21847.04
    1371    2362    2849    4289
River Rch & RM=G103-33-00,G103-33-00_0032     ,21221.31
    1428    2416    2983    4596
River Rch & RM=G103-33-00,G103-33-00_0032     ,13295.80
    2054    2879    3432    5262
River Rch & RM=G103-33-00,G103-33-00_0032     ,11521.57
    2218    3090    3546    5302
River Rch & RM=G103-33-00,G103-33-00_0032     ,9501.098
    2307    3222    3692    5338
River Rch & RM=G103-33-00,G103-33-00_0032     ,7944.210
    2396    3354    3837    5372
River Rch & RM=G103-33-00,G103-33-00_0032     ,6455.492
    3404    4794    5454    7175
Boundary for River Rch & Prof#=G103-33-00,G103-33-00_0032     , 1
Up Type= 0
Dn Type= 3
Dn Slope=.00187
Boundary for River Rch & Prof#=G103-33-00,G103-33-00_0032     , 2
Up Type= 0
Dn Type= 3
Dn Slope=.00187
Boundary for River Rch & Prof#=G103-33-00,G103-33-00_0032     , 3
Up Type= 0
Dn Type= 3
Dn Slope=.00187
Boundary for River Rch & Prof#=G103-33-00,G103-33-00_0032     , 4
Up Type= 0
Dn Type= 3
Dn Slope=.00187
DSS Import GetInterval= 0
DSS Import GetPeak= 0
DSS Import FillOption= 0

--- G103-33-00.g02 (geometry) ---

Geom Title=G103-33-00 June 2007
Version=Version 3.0.1  Mar 2001

River Reach=G103-33-00     ,G103-33-00_0032
Reach XY= 30
     3158111.754     13955925.16       3159079.2    13956397.061
     3161672.982    13956527.873     3162380.576    13955988.895
     3162857.721    13956135.731     3163723.055    13955884.799
     3165810.472    13954817.907     3167222.468    13954853.431
     3168253.822     13953168.01     3168848.543    13952615.892
     3169388.071    13952666.847     3169823.247    13952165.861
     3170666.644    13950357.677     3171715.945      13949952.1
     3172169.297    13949111.543      3172766.02    13948758.599
     3173265.416    13948673.724     3174065.334    13948984.948
      3174376.24     13948831.19     3174944.393    13947493.821
      3176393.61    13945692.386     3176768.174    13945659.345
     3176924.594    13946249.346     3178046.123    13947045.689
     3178490.119    13946042.866     3179258.666    13945764.878
     3179977.857    13944952.528      3180743.89    13944813.754
     3181556.288    13944053.822     3183529.381    13943674.862

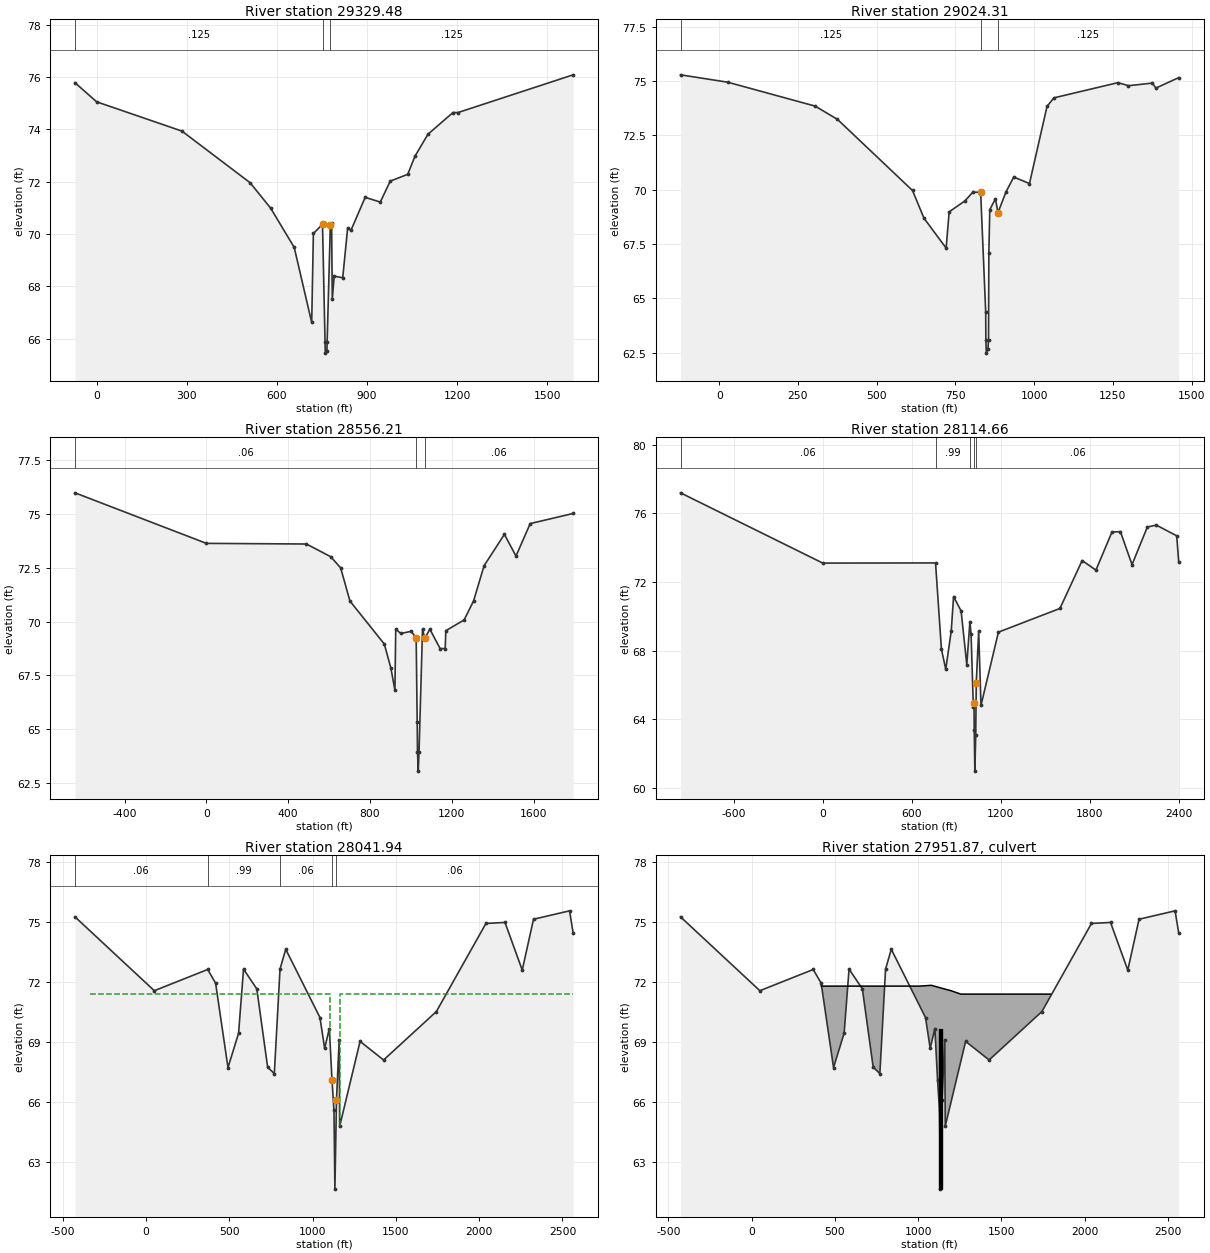
Type RM Length L Ch R = 1 ,29329.48,305.25,305.16,247.13
BEGIN DESCRIPTION:
425v21 - Additional Xsec beyond FIS extents as requested
Bank Station offset =      4562
Cross section extended on LOB and ROB
END DESCRIPTION:
XS GIS Cut Line= 6
 3163284.386521513956813.5308208     3163277.657    13956741.846
     3163210.739    13956029.016     3163196.191    13955962.097
     3163242.743    13955546.037 3163285.319132913955165.5114403
#Sta/Elev= 29
     -72   75.78       0   75.05  284.19   73.93  510.83   71.96  579.16   70.99
  657.73   69.49  715.96   66.62  721.54   70.02  751.94   70.37  760.31   65.89
  761.25   65.45  766.64   65.55  767.32   65.89  778.05   70.36  782.15   70.43
  784.45   67.51  790.75   68.39  819.23   68.33  835.68   70.24  846.59   70.14
  893.89    71.4  944.24   71.22  977.27   72.02 1035.61   72.28 1059.56   72.97
 1102.84   73.81 1186.12   74.64  1203.1   74.64    1586   76.08
#Mann= 3 , 0 , 0
     -72    .125       0  751.94     .07       0  778.05    .125       0
Bank Sta=751.94,778.05
XS Rating Curve= 0
Exp/Cntr=.3,.1

Type RM Length L Ch R = 1 ,29024.31,449.85,468.11,359.52
BEGIN DESCRIPTION:
425v22 - Additional Xsec beyond FIS extents as requested
Bank Station offset =      4384
Extended cross section on LOB
END DESCRIPTION:
XS GIS Cut Line= 5
 3163627.222399513956825.7152847     3163609.341    13956704.022
     3163504.599    13955991.192     3163449.318    13955735.155
     3163324.209    13955275.453
#Sta/Elev= 30
    -123   75.28   27.25   74.94   304.7   73.84   375.5   73.23  613.69   69.96
     650   68.69  720.48   67.31  730.08   68.98  780.08   69.48  805.08   69.88
  830.08   69.88  846.08   64.38  846.58   63.08  848.08   62.48  853.08   62.68
  855.08   63.08  856.08   67.08  859.08   69.08  877.08   69.58  885.08   68.94
  910.08   69.88  935.08   70.58  985.08   70.28 1040.84   73.83 1062.59   74.22
 1265.99   74.92 1299.48   74.78 1375.29    74.9 1386.43   74.67 1458.84   75.15
#Mann= 3 , 0 , 0
    -123    .125       0  830.08     .07       0  885.08    .125       0
Bank Sta=830.08,885.08
XS Rating Curve= 0
Exp/Cntr=.3,.1

Type RM Length L Ch R = 1 ,28556.21,407.25,441.54,331.11
BEGIN DESCRIPTION:
425v23 - Additional Xsec beyond FIS extents as requested
Bank Station offset =      4253
Cross section extended on LOB
END DESCRIPTION:
XS GIS Cut Line= 5
 3164147.554298213957396.3573971     3164060.315    13956759.303
     3163935.207    13955845.717     3163810.098    13955630.413
     3163431.861    13955135.796
#Sta/Elev= 30
    -643   75.99       0   73.64  489.27   73.61  608.05   73.02   656.7    72.5
  702.01   70.96  870.22   68.96  902.39   67.84  922.11   66.81  926.05   69.65
  951.05   69.45 1001.05   69.55 1026.05   69.25 1031.05   65.35 1032.55   63.95
 1036.05   63.05 1040.05   63.95 1057.05   69.65 1068.05   69.22 1093.05   69.65
 1143.05   68.75 1168.05   68.75 1171.13   69.58 1260.56   70.08 1306.73   70.96
 1358.21    72.6 1457.66   74.06 1514.31   73.05 1583.94   74.56 1793.79   75.03
#Mann= 3 , 0 , 0
    -643     .06       0 1026.05     .04       0 1068.05     .06       0
Bank Sta=1026.05,1068.05
XS Rating Curve= 0
Exp/Cntr=.3,.1

Type RM Length L Ch R = 1 ,28114.66,92.81,72.72,72.72
BEGIN DESCRIPTION:
425v1.  Surveyed section.  XS 4/4, 425s10y.
Bank Station offset =      3975
block in right overbank to eliminate distribution of flow in non flowing area
Cross section extended on LOB.
END DESCRIPTION:
XS GIS Cut Line= 5
 3164630.582333513957624.1532385     3164474.719    13956677.904
     3164313.452    13955698.849      3164301.48    13955644.431
     3163247.714    13954798.616
#Sta/Elev= 30
    -959   77.19       0    73.1  760.21   73.11  799.86   68.09  829.13   66.92
  866.13   69.15  881.83   71.15  932.67   70.31  970.92   67.18  991.81   69.69
  999.81   68.96  1015.1   64.72 1019.66   64.93 1021.02   63.37 1025.21   60.99
 1031.07   63.07 1034.72   66.13 1051.01   69.13  1066.7   64.82 1184.07   69.08
 1598.79   70.46 1748.61   73.25 1841.36   72.69 1949.48   74.91 2006.58   74.93
 2084.72   73.01 2188.03    75.2 2248.52   75.31 2385.84   74.69  2399.2   73.19
#Mann= 5 ,-1 , 0
    -959     .06       0  760.21     .99       0  991.81     .06       0
 1019.66     .04       0 1034.72     .06       0
#Block Obstruct= 2 , 0
       0                 2006.58       0   74.93
Bank Sta=1019.66,1034.72
XS Rating Curve= 0
Exp/Cntr=.5,.3

Type RM Length L Ch R = 1 ,28041.94,134.33,180.14,283.29
BEGIN DESCRIPTION:
Copy of 425v1.  XS 3/4, s10x.
Notes:  Adjusted elevations between CB's based on US invert elevation of 425s11. Moved left CB to x-sec sta 1116.37 from 1128.11.
Extended cross-section on LOB.  Set n=0.99 in tributary ditches. (more below)
Bank Station offset =      3866
block in right overbank to eliminate distribution of flow in non flowing area
END DESCRIPTION:
XS GIS Cut Line= 6
 3165106.4974078 13956991.053038 3165062.985871113956912.1102206
     3164368.366    13955651.864     3164361.476    13955620.544
     3164343.325    13955605.118     3163257.955    13954711.566
#Sta/Elev= 30
    -427   75.27   49.51   71.58  369.73   72.64  417.38   71.96  491.84   67.74
  555.44   69.46  585.06   72.66  664.85   71.67  729.85   67.76  769.94   67.44
  804.19   72.66  838.45   73.65 1043.98   70.24 1072.06    68.7 1100.26   69.69
 1116.37   67.11 1128.11   65.61 1133.66   61.67 1143.17   66.13 1159.46   69.13
 1162.36   64.81 1284.81   69.05 1425.84   68.12  1742.9   70.54  2040.5   74.94
 2154.84   74.99 2258.42   72.61 2326.07   75.15 2542.48   75.57  2563.9   74.47
#Mann= 5 ,-1 , 0
    -427     .06       0  369.73     .99       0  804.19     .06       0
 1116.37     .04       0 1143.17     .06       0
#XS Ineff= 2 , 0
 -336.86 1103.14   71.41 1163.14 -336.86   71.41
Permanent Ineff=
       F       F
#Block Obstruct= 2 , 0
       0                 2154.84       0      76
Bank Sta=1116.37,1143.17
XS Rating Curve= 0
Exp/Cntr=.5,.3

Type RM Length L Ch R = 2 ,27951.87,,,
BEGIN DESCRIPTION:
425s11: West North Park Drive (2-9' x 8' Conc. Box Culverts)
END DESCRIPTION:
Bridge Culvert--1,0,-1,-1, 0
Deck Dist Width WeirC Skew NumUp NumDn MinLoCord MaxHiCord MaxSubmerge Is_Ogee
39.32,101.5,2.6,0, 7, 5, 71.41, , .95, 0, 0,0,,
     419 1009.91 1078.84 1147.92 1196.85 1256.04    1795
   71.81   71.81   71.85   71.69   71.58   71.41   71.41
                                                        
     150 1140.08 1180.23 1229.63    1735
   71.67   71.67   71.38   71.37   71.37
                                        
BR Coef=-1 , 0 , 0 ,, 0 ,,,.8,0,,0,
WSPro=,,,, 1 ,,,, 0 ,,,, 0 ,,,,-1 ,-1 ,-1 , 0 , 0 , 0 , 0 , 0
Multiple Barrel Culv=2,8,9,164,.012,.4,1,8,1,61.67,59.92, 2,2-9'x8'     , 0 ,5.32
 1128.84 1175.41 1138.49 1185.06
Culvert Bottom n=.012
BC Design=,, 0 ,, 0 ,,,,,,

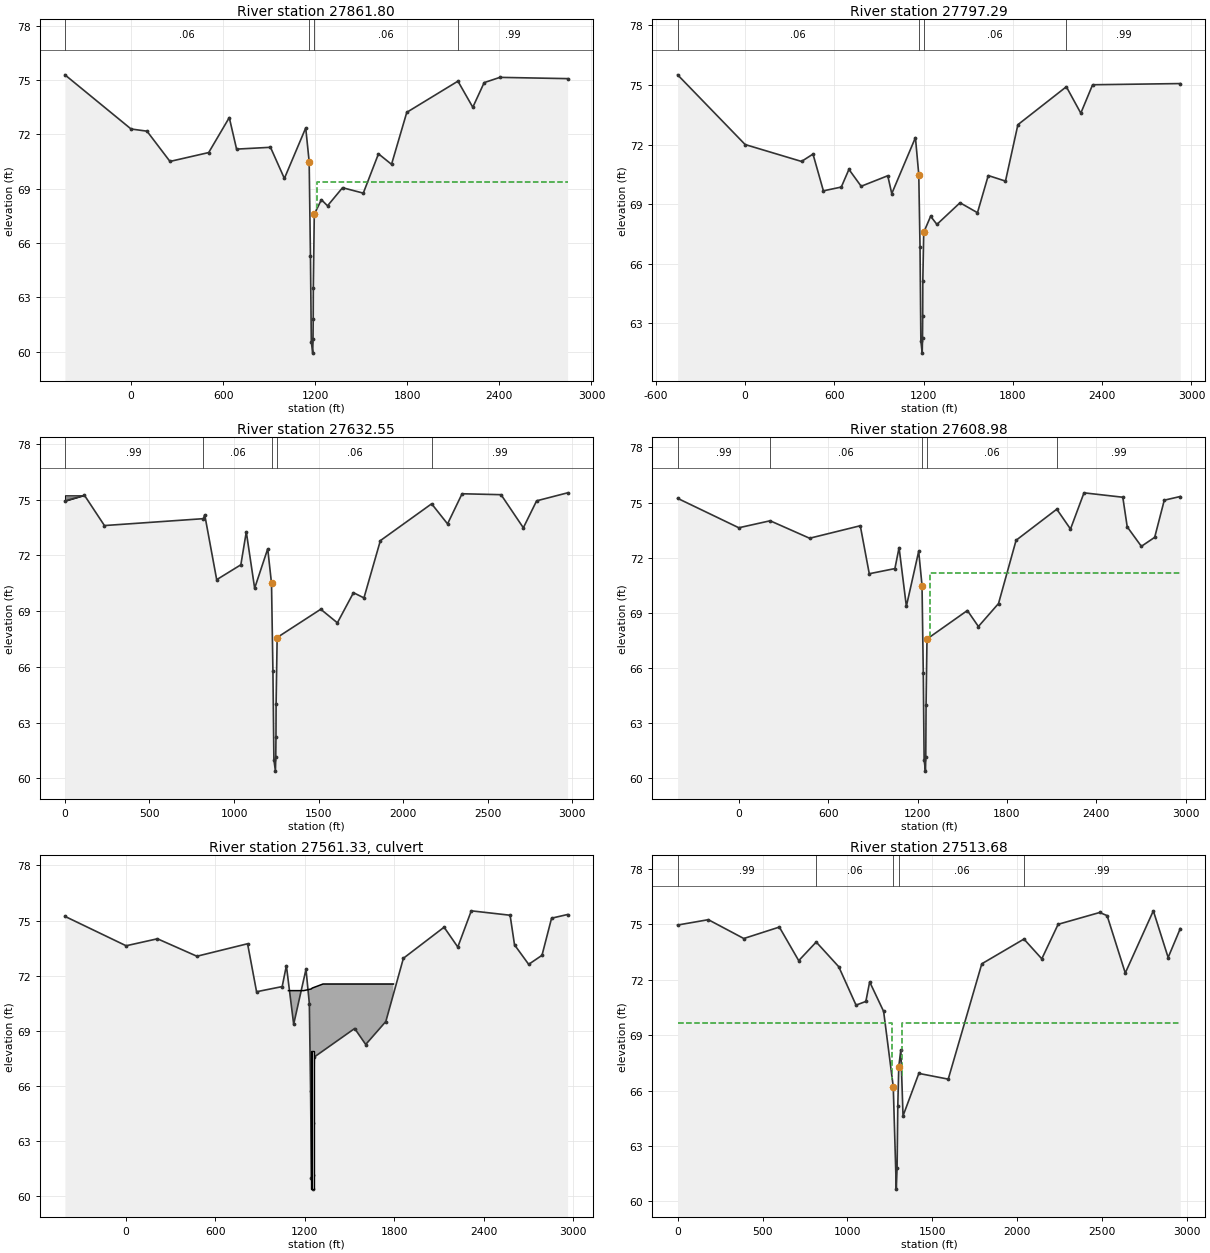
Type RM Length L Ch R = 1 ,27861.80,64.5,64.5,28.15
BEGIN DESCRIPTION:
Copy of 425s10yd.  XS 2/4 s10y.
Notes: Adjusted elevations between CB's based on DS invert elevation of 425s11.
Deleted low LIDAR points on left channel edge, based on survey data, aerial photo, and reconnaissance info. Added special ineffective "n" value.  (more below)
Bank Station offset =      3816
Cross section extended on LOB
END DESCRIPTION:
XS GIS Cut Line= 6
 3165299.442808913956908.1267123      3164508.91    13955635.068
     3164491.254     13955575.34     3164505.638    13955425.634
     3164395.968     13955351.55     3163270.756    13954465.779
#Sta/Elev= 30
    -431   75.28       0   72.29  103.82   72.17  253.62    70.5  505.87   70.99
  639.98   72.92  687.65   71.18   908.6   71.28  999.12   69.56 1138.18   72.35
  1160.6   70.49 1168.96   65.28 1174.68   60.54 1183.67   59.92 1185.78    60.7
 1186.94   61.78 1187.74   63.54 1193.93   67.58 1240.28   68.39 1280.23   68.05
 1378.19   69.05  1513.3   68.75  1612.3   70.92 1697.34   70.34 1796.77   73.21
 2129.99   74.93 2226.99   73.49 2300.98   74.85 2403.64   75.14  2844.6   75.07
#Mann= 4 ,-1 , 0
    -431     .06       0  1160.6     .04       0 1193.93     .06       0
 2129.99     .99       0
#XS Ineff= 2 , 0
       0    1145   69.37    1210       0   69.37
Permanent Ineff=
       F       F
Bank Sta=1160.6,1193.93
XS Rating Curve= 0
Exp/Cntr=.5,.3

Type RM Length L Ch R = 1 ,27797.29,269.17,164.74,29.83
BEGIN DESCRIPTION:
425s10yd.  Surveyed section.  XS 1/4 s10y.
Deleted low LIDAR points on left channel edge, based on survey data, aerial photo, and reconnaissance info.
Bank Station offset =      3810
Cross section extended on LOB
END DESCRIPTION:
XS GIS Cut Line= 6
 3165532.231598413956838.2384367     3164571.909    13955646.652
     3164554.253    13955586.924     3164568.637    13955437.218
     3164458.967    13955363.134     3163275.877    13954435.055
#Sta/Elev= 30
    -454   75.51       0      72  378.79   71.15  456.04   71.52  525.92   69.67
  646.24   69.86  697.57   70.75  779.86    69.9  958.65   70.43  985.55   69.53
  1144.7   72.35 1167.12   70.49 1175.48   66.86  1181.2   62.12 1190.19    61.5
  1192.3   62.28 1193.46   63.36 1194.26   65.12 1200.45   67.58  1246.8   68.39
 1289.08   67.98 1444.44   69.07 1561.72   68.57  1634.2   70.44 1750.02   70.16
 1833.47      73 2159.16   74.91 2256.38   73.58 2335.72   75.01 2925.11   75.07
#Mann= 4 ,-1 , 0
    -454     .06       0 1167.12     .04       0 1200.45     .06       0
 2159.16     .99       0
Bank Sta=1167.12,1200.45
XS Rating Curve= 0
Exp/Cntr=.3,.1

Type RM Length L Ch R = 1 ,27632.55,23.57,23.57,23.57
BEGIN DESCRIPTION:
Copy of 425s10yd.   XS 4/4, s10z.
Notes: Adjusted elevations between CB's based on US invert elevation of 425s10. Deleted low LIDAR points on left channel edge, based on survey data, aerial photo, and reconnaissance info.
Added special ineffective "n" value.
Bank Station offset =      3755
END DESCRIPTION:
XS GIS Cut Line= 6
     3165509.523    13956375.466     3164790.337    13955501.616
     3164753.692    13955469.283      3164654.15    13955433.688
     3164533.009    13955387.236     3163333.439    13954395.537
#Sta/Elev= 30
       0   74.92  115.34   75.23  233.65    73.6   818.6   73.97  826.66   74.18
  897.49   70.69 1040.32   71.49 1072.53   73.26 1121.93   70.23 1199.27   72.35
 1221.69   70.49 1230.05  65.755 1235.77  61.015 1244.76  60.395 1246.87  61.175
 1248.03  62.255 1248.83  64.015 1255.02   67.58 1512.88    69.1 1611.17   68.37
 1706.36   69.99 1768.32   69.71 1865.41   72.79 2168.52   74.77 2262.69   73.69
 2348.57   75.31 2579.02   75.26 2710.87   73.48 2789.44   74.93 2972.49   75.36
#Mann= 5 ,-1 , 0
       0     .99       0   818.6     .06       0 1221.69     .04       0
 1255.02     .06       0 2168.52     .99       0
#Block Obstruct= 2 , 0
       0  115.34   75.23               0
Bank Sta=1221.69,1255.02
XS Rating Curve= 0
Exp/Cntr=.5,.3

Type RM Length L Ch R = 1 ,27608.98,95.3,95.3,134.23
BEGIN DESCRIPTION:
Copy of 425s10yd.   XS 3/4, s10z.
Bank Station offset =      3747
Notes: Adjusted elevations between CB's based on US invert elevation of 425s10. Deleted low LIDAR points on left channel edge, based on survey data, aerial photo, and reconnaissance info.
Added special ineffective "n" value. (more below)
Block in right overbank to eliminate flow being located in an area outside of the flow area
Cross section extended on LOB
END DESCRIPTION:
XS GIS Cut Line= 6
 3165831.294846513956641.5917099     3164843.603    13955506.555
     3164768.915    13955444.618     3164671.456    13955427.312
     3164543.028    13955366.286     3163380.544    13954367.274
#Sta/Elev= 30
    -411   75.23       0   73.63  210.31   74.01  475.34   73.06  815.64   73.74
  876.04   71.13 1048.08   71.41 1076.14   72.55 1125.13   69.36 1207.89   72.35
 1230.31   70.49 1238.67  65.755 1244.39  61.015 1253.38  60.395 1255.49  61.175
 1257.45  64.015 1263.64   67.58  1534.8   69.13 1608.91   68.26 1744.04   69.51
 1862.03   72.95 2135.28   74.64 2227.34   73.56 2317.98   75.53 2578.65   75.29
 2608.27   73.68 2703.27   72.62 2792.73   73.11 2857.14   75.13 2964.61   75.33
#Mann= 5 ,-1 , 0
    -411     .99       0  210.31     .06       0 1230.31     .04       0
 1263.64     .06       0 2135.28     .99       0
#XS Ineff= 2 , 0
       0    1215   71.19    1285       0   71.19
Permanent Ineff=
       F       F
#Block Obstruct= 2 , 0
       0                 2317.98       0   75.53
Bank Sta=1230.31,1263.64
XS Rating Curve= 0
Exp/Cntr=.5,.3

Type RM Length L Ch R = 2 ,27561.33,,,
BEGIN DESCRIPTION:
425s10: East North Park Drive (2-9' x 7.5' Conc. Box Culverts)
END DESCRIPTION:
Bridge Culvert--1,0,-1,-1, 0
Deck Dist Width WeirC Skew NumUp NumDn MinLoCord MaxHiCord MaxSubmerge Is_Ogee
35.65,24,2.6,0, 6, 6, 71.19, , .95, 0, 0,0,,
    1090 1192.56 1242.61 1249.94 1322.02    1795
   71.19   71.19   71.28   71.33   71.55   71.55
                                                
    1020 1230.71 1280.76 1288.09 1360.17    1745
   71.19   71.19   71.28   71.33   71.55   71.55
                                                
BR Coef=-1 , 0 , 0 ,, 0 ,,,.8,0,,0,
WSPro=,,,, 1 ,,,, 0 ,,,, 0 ,,,,-1 ,-1 ,-1 , 0 , 0 , 0 , 0 , 0
Multiple Barrel Culv=2,7.5,9,59.04,.012,.4,1,8,1,60.395,60.66, 2,2-9'x7.5'   , 0 ,18.15
 1245.09 1283.24 1254.79 1292.94
Culvert Bottom n=.012
BC Design=,, 0 ,, 0 ,,,,,,

Type RM Length L Ch R = 1 ,27513.68,33.69,71.99,95.59
BEGIN DESCRIPTION:
Copy of 425v2.  XS 2/4, s10z.
Bank Station offset =      3712
Notes: Adjusted elevations between CB's based on DS invert elevation of 425s10. Moved right CB to x-sec sta 1302.65 from 1296.9 based on right CB elev at nearest US x-section. (more below)
Block in right overbank to eliminate flow being located in an area outside of the flow area
END DESCRIPTION:
XS GIS Cut Line= 5
      3165855.76    13956067.162      3164821.67    13955366.761
     3164777.051    13955362.163     3164743.416    13955357.781
     3163467.003    13954338.932
#Sta/Elev= 30
       0   74.97  180.85   75.26  389.87   74.24  599.21   74.86   713.3   73.04
  816.45   74.05  949.15   72.71 1050.96   70.63 1108.74   70.83  1131.2   71.89
 1213.49   70.29 1270.23   66.21 1288.09   60.66 1292.76   61.82  1296.9   65.15
 1302.65   67.29 1314.88   68.21 1327.74   64.63 1420.93   66.93 1594.05   66.62
 1791.77   72.87 2040.02   74.21 2145.22   73.14  2241.4   75.01 2486.27   75.65
 2529.93   75.48 2636.93   72.37  2802.2   75.74 2889.43   73.21 2960.92   74.78
#Mann= 5 ,-1 , 0
       0     .99       0  816.45     .06       0 1270.23     .04       0
 1302.65     .06       0 2040.02     .99       0
#XS Ineff= 2 , 0
       0    1265   69.68    1320       0   69.68
Permanent Ineff=
       F       F
#Block Obstruct= 2 , 0
       0                 2486.27       0   75.65
Bank Sta=1270.23,1302.65
XS Rating Curve= 0
Exp/Cntr=.5,.3

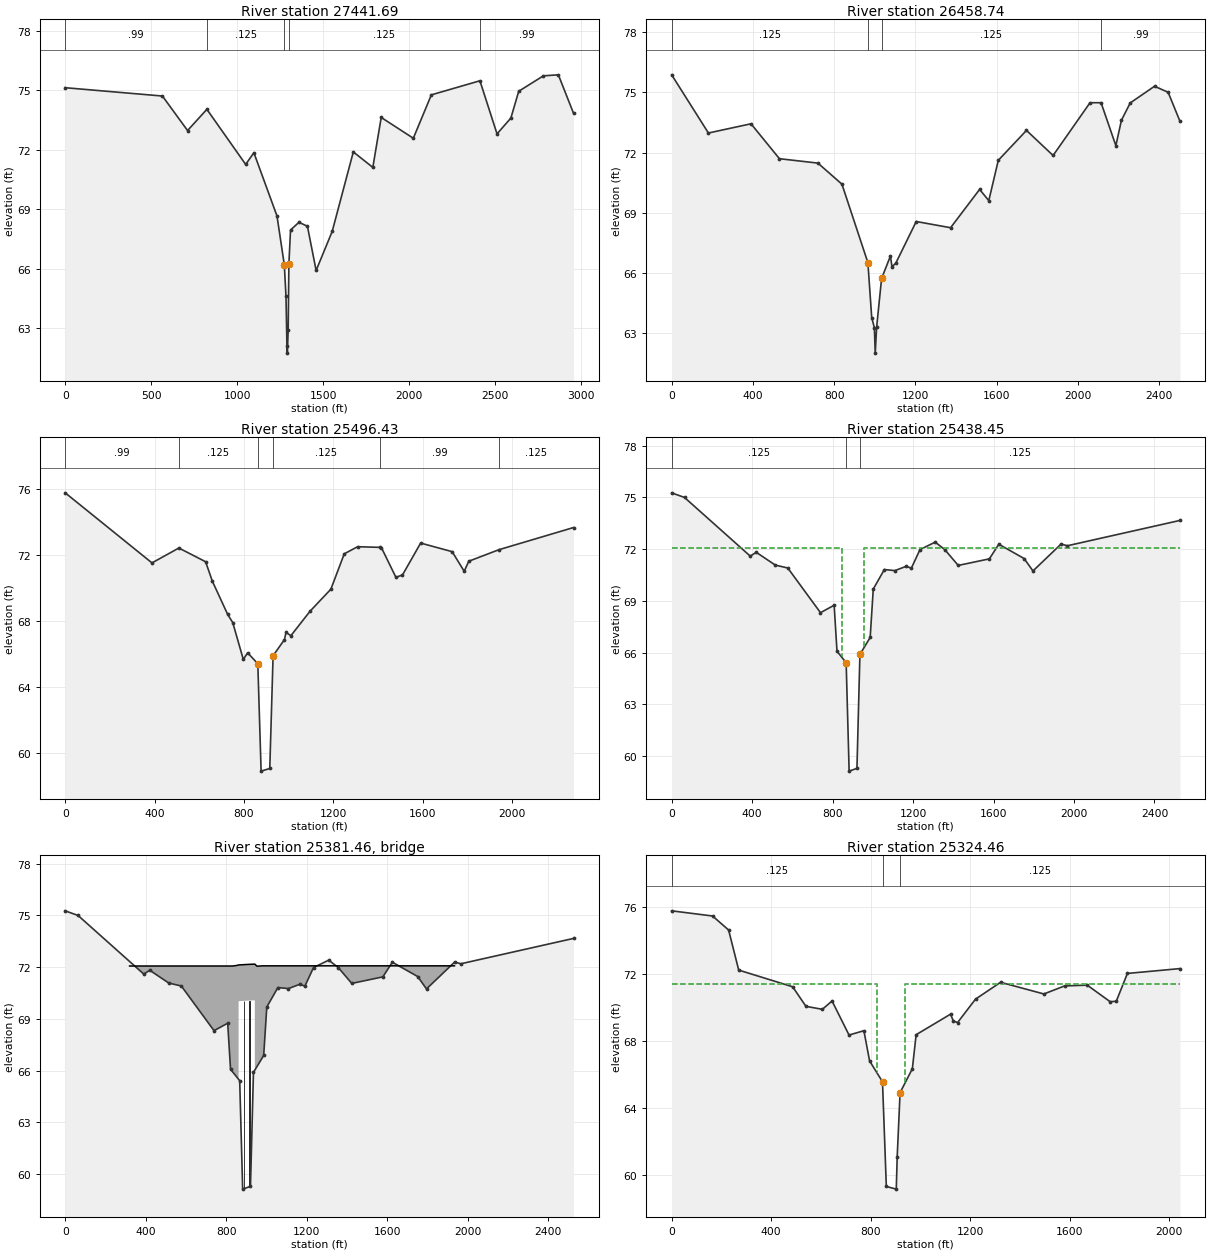
Type RM Length L Ch R = 1 ,27441.69,950.19,982.95,1017.11
BEGIN DESCRIPTION:
425v2.  Surveyed section.  XS 1/4, s10z.
Bank Station offset =      3708
END DESCRIPTION:
XS GIS Cut Line= 4
     3165905.832    13956016.307     3164856.609    13955352.135
     3164814.068    13955293.232     3163517.075    13954288.078
#Sta/Elev= 30
       0   75.14  565.24   74.72  711.36   72.98  823.58   74.05 1049.22   71.27
 1096.94   71.86 1231.26   68.67 1273.74   66.21 1283.62   64.61 1289.08   62.11
  1291.6   61.75 1296.27   62.91 1300.41   66.24 1309.98   67.96 1358.99   68.35
 1408.18   68.15  1458.8   65.92 1552.25   67.89 1674.97    71.9 1788.46   71.12
 1837.24   73.64 2023.85   72.59 2128.76   74.78 2411.08   75.49 2510.51   72.81
 2591.09   73.61 2636.63   74.96 2780.08   75.74 2867.07   75.79 2955.32   73.85
#Mann= 5 ,-1 , 0
       0     .99       0  823.58    .125       0 1273.74     .07       0
 1300.41    .125       0 2411.08     .99       0
#Block Obstruct= 2 , 0
       0                 2867.07       0   75.79
Bank Sta=1273.74,1300.41
XS Rating Curve= 0
Exp/Cntr=.3,.1

Type RM Length L Ch R = 1 ,26458.74,876.94,962.31,1105.4
BEGIN DESCRIPTION:
425v3
Bank Station offset =      3998
END DESCRIPTION:
XS GIS Cut Line= 4
     3166113.944    13955808.196     3165730.342    13954949.629
     3165655.077    13954841.639     3164883.372    13953636.598
#Sta/Elev= 30
       0   75.88  180.92   72.98  390.65   73.44  530.54    71.7   720.2   71.48
  838.32   70.43  966.14   66.52  984.98   63.78  998.07   63.28  1002.3   62.01
 1009.19    63.3  1033.6   65.73 1077.25   66.85 1084.75   66.31 1103.89    66.5
  1204.2   68.57 1373.31   68.26  1516.3   70.17 1561.48   69.61 1608.31   71.62
 1747.02   73.11 1878.05   71.86 2059.92   74.49 2114.29   74.49 2187.14   72.35
 2214.69   73.62 2258.06   74.48 2377.54   75.31 2444.55   75.01 2502.96   73.56
#Mann= 4 ,-1 , 0
       0    .125       0  966.14     .07       0  1033.6    .125       0
 2114.29     .99       0
#Block Obstruct= 2 , 0
       0                 2377.54       0   75.31
Bank Sta=966.14,1033.6
XS Rating Curve= 0
Exp/Cntr=.3,.1

Type RM Length L Ch R = 1 ,25496.43,57.98,57.98,57.98
BEGIN DESCRIPTION:
425s9u.  Surveyed section.  XS 4/4.
Bank Station offset =      4108
Cross section extended on ROB
END DESCRIPTION:
XS GIS Cut Line= 6
     3166557.311    13955835.341      3166610.62    13955015.077
     3166633.527    13954864.546     3166611.601    13954360.464
     3166624.316    13953897.232 3166633.474294813953563.5776375
#Sta/Elev= 30
       0   75.76  388.45   71.52  508.91   72.42  628.67   71.59  658.93   70.41
  727.54    68.4  750.11   67.91  797.38   65.68  816.86   66.08  862.35   65.42
  877.14   58.92  915.99   59.08  930.75    65.9  981.71   66.88  988.55   67.31
 1010.74   67.12 1095.88   68.59  1189.5   69.93 1249.46   72.07 1309.32    72.5
  1408.9   72.46 1415.58   72.45 1480.61   70.65 1510.15   70.79 1591.52   72.72
 1732.54    72.2  1786.6   71.01 1806.81   71.62 1942.22   72.32    2276   73.66
#Mann= 6 ,-1 , 0
       0     .99       0  508.91    .125       0  862.35     .04       0
  930.75    .125       0  1408.9     .99       0 1942.22    .125       0
Bank Sta=862.35,930.75
XS Rating Curve= 0
Exp/Cntr=.5,.3

Type RM Length L Ch R = 1 ,25438.45,113.99,113.99,113.99
BEGIN DESCRIPTION:
Copy of 425s9u.  XS 3/4.
 Notes: Adjusted elevations between CB's based on invert elevation of 425s9.
Bank Station offset =      4103
Cross section extended on ROB
END DESCRIPTION:
XS GIS Cut Line= 6
     3166613.892    13955848.812       3166667.2    13955028.548
     3166690.107    13954878.018      3166682.71    13954376.059
     3166694.388    13953885.553 3166707.718643913953325.6317099
#Sta/Elev= 30
       0   75.27    63.9      75  390.58    71.6   420.5   71.82   515.1   71.08
  577.27   70.91  739.76   68.32  807.71   68.75  821.92   66.08  867.41   65.42
   882.2   59.13  921.05   59.29  935.81    65.9  986.77   66.88 1002.17   69.69
 1057.27   70.82 1109.49   70.76 1166.61   71.01 1191.47    70.9 1234.51   71.98
 1310.13   72.41 1357.51   71.98 1424.52   71.06 1579.24   71.44 1626.23   72.29
    1752   71.46 1796.08   70.74 1935.96    72.3 1966.92    72.2    2527   73.67
#Mann= 3 , 0 , 0
       0    .125       0  867.41     .04       0  935.81    .125       0
#XS Ineff= 2 , 0
       0  846.33   72.06   958.3       0   72.06
Permanent Ineff=
       F       F
Bank Sta=867.41,935.81
XS Rating Curve= 0
Exp/Cntr=.5,.3

Type RM Length L Ch R = 3 ,25381.46,,,
BEGIN DESCRIPTION:
Woodland Hills Northbound and Southbound; 425s8 & 425s9:
425s8:Woodland Hills North Bound Lane
425s9:Woodland Hills South Bound Lane
Notes:Extended bridge deck on LOB to x-sec sta 320 @  US & DS cross sections. Extended bridge deck on ROB to x-sec sta 1935 US and 1870 DS.
END DESCRIPTION:
Bridge Culvert--1,0,-1,-1, 0
Deck Dist Width WeirC Skew NumUp NumDn MinLoCord MaxHiCord MaxSubmerge Is_Ogee
12.99,88,2.6,0, 9, 7, 72.06, , .95, 0, 0,0,,
     320  831.72  852.14  861.94  903.96   942.7  953.12  981.26    1935
   72.07   72.07    72.1   72.13   72.16   72.18   72.06   72.08   72.08
                           70.03   70.06   70.08
     320  830.08  840.68  881.94  921.62  931.42    1870
   72.07   71.97   72.08   72.16   72.14   72.09   72.09
                   70.08   70.16   70.14
Pier Skew, UpSta & Num, DnSta & Num=  ,888.285, 4 ,869.805, 4 , 3 , 3 , 0 ,,
    1.35    1.35     2.2     2.2
      58   67.86   67.86   70.06
    1.35    1.35     2.2     2.2
      58   67.93   67.93   70.13
Pier Skew, UpSta & Num, DnSta & Num=  ,915.395, 4 ,896.915, 4 , 3 , 3 , 0 ,,
    1.35    1.35     2.2     2.2
      58   67.86   67.86   70.06
    1.35    1.35     2.2     2.2
      58   67.93   67.93   70.13
BR Coef=-1 , 0 , 0 ,, 0 ,,,.8,-1,,0,
WSPro=,,,, 1 ,,,, 0 ,,,, 0 ,,,,-1 ,-1 ,-1 , 0 , 0 , 0 , 0 , 0
BC Design=,, 0 ,, 0 ,,,,,,

Type RM Length L Ch R = 1 ,25324.46,44.95,44.95,44.95
BEGIN DESCRIPTION:
Copy of 425s8d.  XS 2/4.
Notes: Adjusted elevations between CB's based on invert elevation of 425s8.
Higher ineffective elevations used to maintain consistently ineffective 0.2% profile along xsec 2/4, internal & 3/4 (This causes the -ve slope in 0.2% profile >0.05)
Extended cross section on ROB
The high point on ROB dividing the 100yr flow does not make the flow ineffective. Hence n=0.99 not used.
Bank Station offset =      4097
END DESCRIPTION:
XS GIS Cut Line= 6
     3166829.098    13955837.137     3166798.056    13955043.052
     3166791.511    13954882.704      3166803.39    13954372.166
     3166818.961    13953889.446 3166822.029607413953794.3154251
#Sta/Elev= 30
       0    75.8  164.41   75.49  228.96   74.65  269.54   72.25  486.56   71.25
   539.8   70.08  605.93    69.9  644.83    70.4  713.16   68.36  772.95   68.62
   795.8   66.81  847.74   65.56  863.15   59.29  903.14   59.13  906.87   61.08
  918.42   64.91  967.72   66.34  982.99   68.38 1121.24   69.61 1132.73    69.2
 1149.67   69.11 1221.73   70.51 1322.54   71.52 1496.65   70.82 1579.72    71.3
  1670.9   71.35 1762.87   70.36 1787.68   70.38 1832.56   72.05    2044   72.34
#Mann= 3 , 0 , 0
       0    .125       0  847.74     .04       0  918.42    .125       0
#XS Ineff= 2 , 0
       0  825.07    71.4  937.34       0    71.4
Permanent Ineff=
       F       F
Bank Sta=847.74,918.42
XS Rating Curve= 0
Exp/Cntr=.5,.3

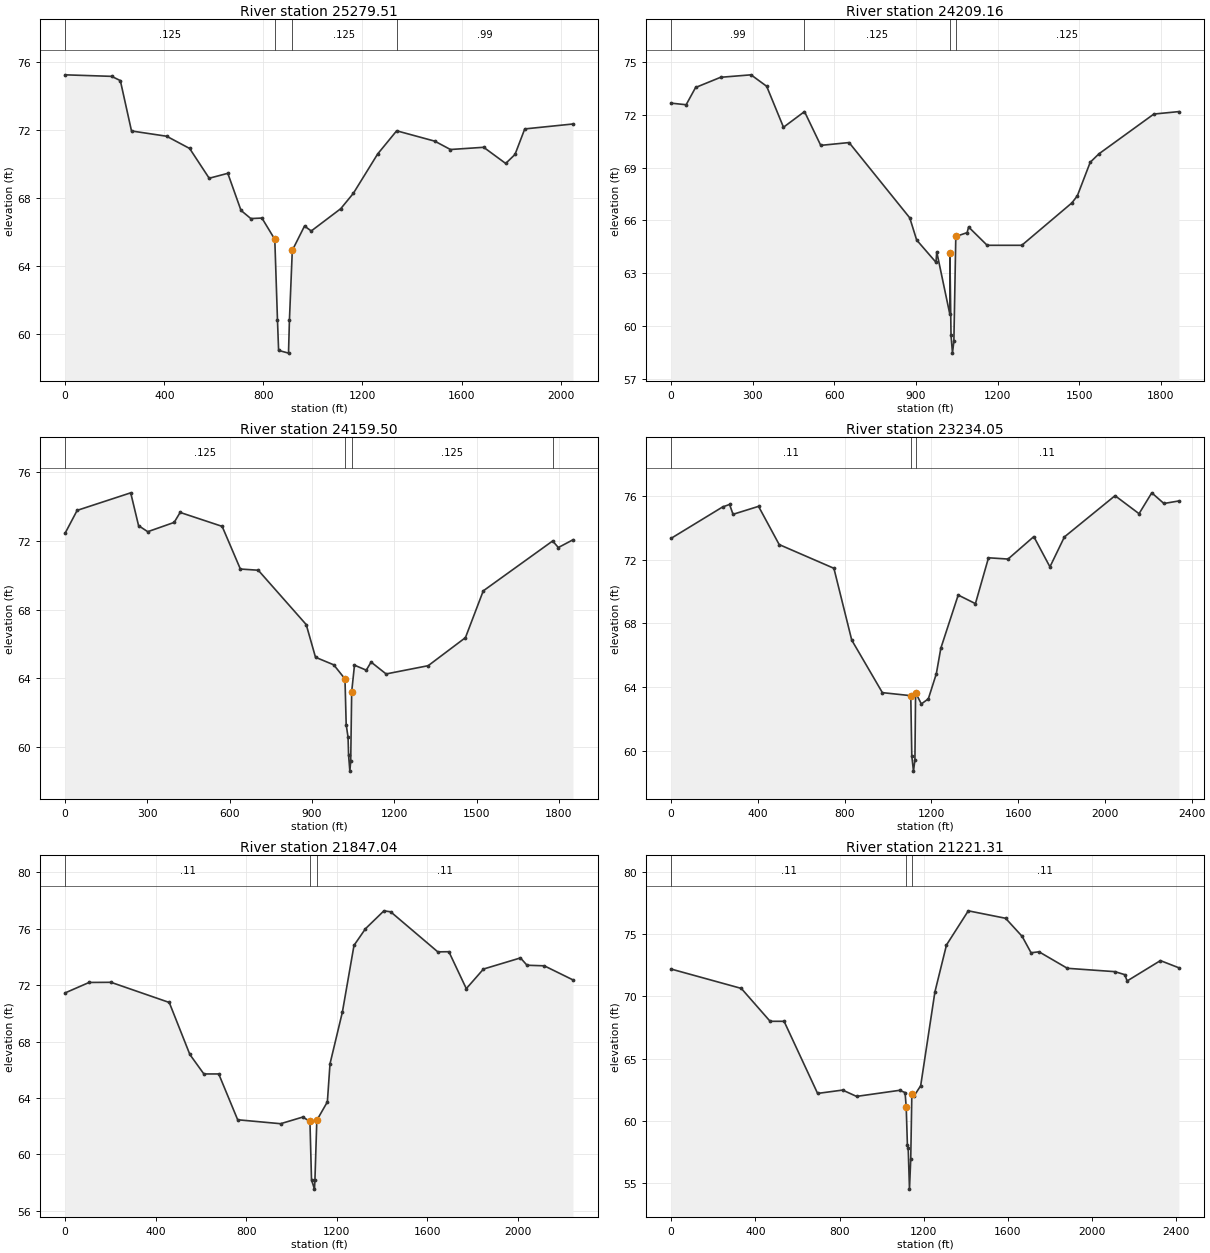
Type RM Length L Ch R = 1 ,25279.51,1179.88,1070.35,917.2
BEGIN DESCRIPTION:
425s8d.  Surveyed section.  XS 1/4.
Bank Station offset =      4098
Extended cross section on ROB
The high point on ROB dividing the 100yr flow does not make the flow ineffective. Hence n=0.99 not used.
END DESCRIPTION:
XS GIS Cut Line= 6
     3166874.003    13955835.341     3166842.961    13955041.256
     3166836.416    13954880.908      3166857.89    13954344.916
     3166853.997    13953877.767 3166853.236675313953786.5301778
#Sta/Elev= 30
       0   75.23  187.66   75.14  222.71   74.89  267.75   71.93  409.66   71.62
  502.49    70.9  581.32   69.15  656.51   69.44  709.77   67.26  749.44   66.78
  794.24   66.81  846.18   65.56  857.08   60.79  861.59   59.03  901.58   58.87
  905.31   60.82  916.86   64.91  966.16   66.34  993.36   66.05 1112.35   67.36
 1163.12   68.26 1261.59   70.58 1338.18   71.94 1492.19   71.33 1555.16   70.84
 1689.53   70.97  1778.3   70.02 1815.95   70.55 1855.27   72.05    2050   72.34
#Mann= 4 ,-1 , 0
       0    .125       0  846.18     .04       0  916.86    .125       0
 1338.18     .99       0
Bank Sta=846.18,916.86
XS Rating Curve= 0
Exp/Cntr=.3,.1

Type RM Length L Ch R = 1 ,24209.16,49.66,49.66,49.66
BEGIN DESCRIPTION:
425v4
Bank Station offset =      3966
END DESCRIPTION:
XS GIS Cut Line= 4
     3168475.556    13954830.977     3167631.611    13954334.416
     3167533.439    13954291.875     3166877.355    13953869.981
#Sta/Elev= 30
       0   72.67   55.38   72.58   90.06   73.56  182.08   74.14  293.75   74.28
  351.26   73.63   413.1    71.3  490.31   72.19  549.99   70.27  654.12   70.43
  877.12   66.15   902.5   64.89  973.65   63.62  976.26   64.22 1024.41   60.67
 1024.55   64.15 1028.79   59.48 1034.13   58.46 1039.28   59.14 1046.39   65.09
 1088.02   65.31 1093.37   65.63 1161.59   64.59 1288.86   64.59 1472.96      67
 1492.94    67.4 1540.33   69.31 1572.46   69.79 1774.17   72.05 1866.21   72.19
#Mann= 4 ,-1 , 0
       0     .99       0  490.31    .125       0 1024.55     .04       0
 1046.39    .125       0
Bank Sta=1024.55,1046.39
XS Rating Curve= 0
Exp/Cntr=.3,.1

Type RM Length L Ch R = 1 ,24159.50,857.75,925.45,964.61
BEGIN DESCRIPTION:
425v5
Bank Station offset =      3962
END DESCRIPTION:
XS GIS Cut Line= 4
     3168547.942    13954713.349     3167661.063    13954298.419
     3167559.618    13954246.061     3166912.391    13953850.517
#Sta/Elev= 30
       0   72.45   43.66   73.77  238.94   74.79  267.65   72.88  301.11   72.53
  397.43   73.07  419.22   73.65  572.43   72.84  638.85   70.36   704.1   70.29
     879   67.13  912.85   65.23  979.42   64.79 1020.36   63.97 1024.72   61.32
 1031.54   60.58 1033.48   59.53 1038.14   58.61 1041.29   59.21 1044.77   63.22
 1054.99   64.77 1097.99   64.48 1115.56   64.95 1170.32   64.26 1323.77   64.74
 1459.59   66.37  1524.6   69.09 1777.52   71.99 1798.42   71.61 1851.83   72.06
#Mann= 4 ,-1 , 0
       0    .125       0 1020.36     .04       0 1044.77    .125       0
 1777.52     .99       0
Bank Sta=1020.36,1044.77
XS Rating Curve= 0
Exp/Cntr=.3,.1

Type RM Length L Ch R = 1 ,23234.05,1183.31,1387.01,1497.11
BEGIN DESCRIPTION:
425v6
Bank Station offset =      3883
END DESCRIPTION:
XS GIS Cut Line= 6
     3168873.682    13954134.256     3168248.725    13953672.149
     3168017.755    13953516.314     3167909.766    13953450.866
     3167498.337    13953075.602     3167091.162    13952632.235
#Sta/Elev= 30
       0   73.34  237.19   75.31  269.68   75.47  285.57   74.85   403.2   75.35
  498.37   72.95  750.59   71.46  832.82   66.95   974.1   63.65 1104.94   63.46
 1109.68   59.68  1117.4   58.72 1124.08   59.43 1127.17   63.65 1153.69   62.94
 1185.94   63.26 1222.83   64.84 1243.54   66.44 1323.62   69.78 1402.99   69.24
 1463.27   72.12 1553.33   72.04 1672.13   73.45 1746.51   71.55 1813.23   73.43
 2046.64   76.02 2157.29   74.89 2215.92    76.2 2271.89   75.53 2340.98   75.69
#Mann= 3 , 0 , 0
       0     .11       0 1104.94     .06       0 1127.17     .11       0
Bank Sta=1104.94,1127.17
XS Rating Curve= 0
Exp/Cntr=.3,.1

Type RM Length L Ch R = 1 ,21847.04,753.06,625.73,568.33
BEGIN DESCRIPTION:
425v7
Bank Station offset =      3899
END DESCRIPTION:
XS GIS Cut Line= 5
     3169127.035    13953718.033     3168953.664    13952711.302
     3168943.847    13952577.133     3168898.033    13952096.089
     3168765.413    13951506.989
#Sta/Elev= 30
       0   71.46  105.65    72.2  202.43   72.21  459.69   70.78  550.74   67.09
   612.6   65.71  678.22   65.71  761.94   62.46  951.61   62.18 1049.17   62.65
 1081.19   62.35  1088.1   58.21  1101.1   57.54 1103.27   58.21 1111.54   62.42
  1158.2   63.73  1169.8   66.43 1224.51    70.1 1275.82   74.83 1326.45   76.01
 1408.05   77.28  1437.8   77.21 1645.96   74.37  1694.9   74.38 1771.85   71.76
 1847.65   73.15 2011.17   73.94 2040.02   73.42 2116.31   73.38 2243.14   72.38
#Mann= 3 , 0 , 0
       0     .11       0 1081.19     .06       0 1111.54     .11       0
Bank Sta=1081.19,1111.54
XS Rating Curve= 0
Exp/Cntr=.3,.1

Type RM Length L Ch R = 1 ,21221.31,1342.1,1673.06,1236.27
BEGIN DESCRIPTION:
425v8
Bank Station offset =      3868
END DESCRIPTION:
XS GIS Cut Line= 5
     3170267.124    13953392.294     3169581.966    13952606.584
     3169473.977    13952521.502     3169090.842    13952044.094
      3168788.77    13951503.096
#Sta/Elev= 30
       0   72.21  333.46   70.65   470.4      68  536.69      68   695.9   62.19
  814.78   62.46  880.87   61.95  1085.1   62.44 1111.24   62.26 1116.63   61.12
 1122.38   58.03    1126   57.83 1132.23   54.48 1138.22   56.92 1143.45   62.16
 1153.74   61.98  1185.4   62.81 1253.04   70.37 1307.97   74.15 1411.55    76.9
 1588.72    76.3 1667.36   74.84 1709.71   73.52 1747.38    73.6 1882.02   72.27
 2107.77      72 2154.36   71.76 2166.04   71.25 2323.99   72.89 2411.72   72.31
#Mann= 3 , 0 , 0
       0     .11       0 1116.63     .06       0 1143.45     .11       0
Bank Sta=1116.63,1143.45
XS Rating Curve= 0
Exp/Cntr=.3,.1