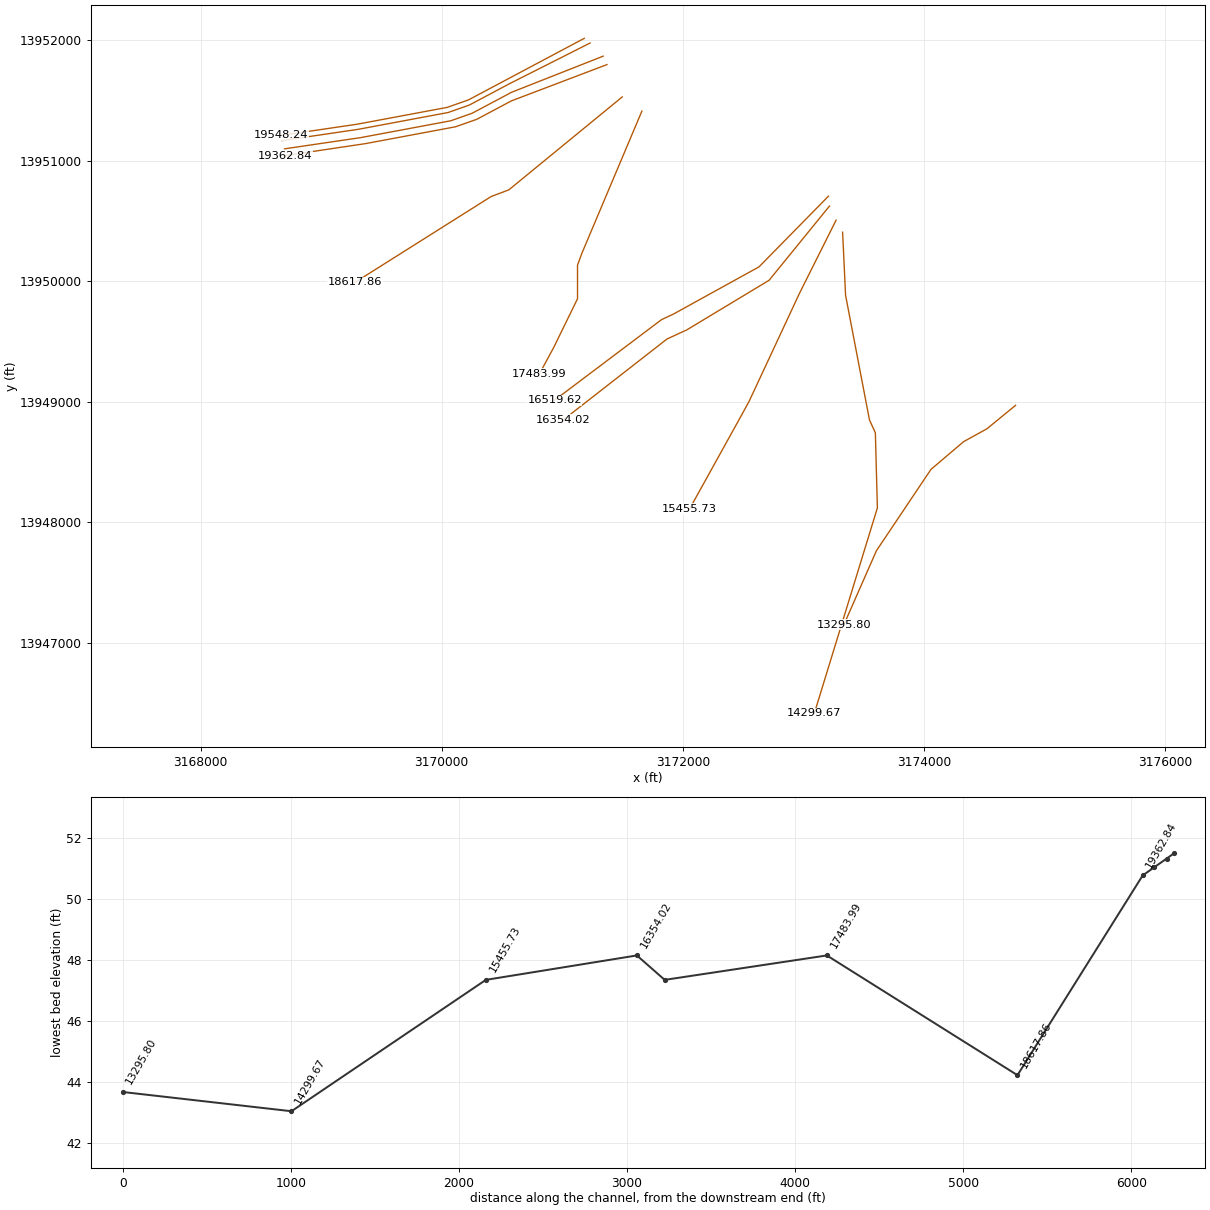
HEC-RAS study G103-33-00.prj: G103-33-00

--- G103-33-00.g02 (geometry) --- (continued)

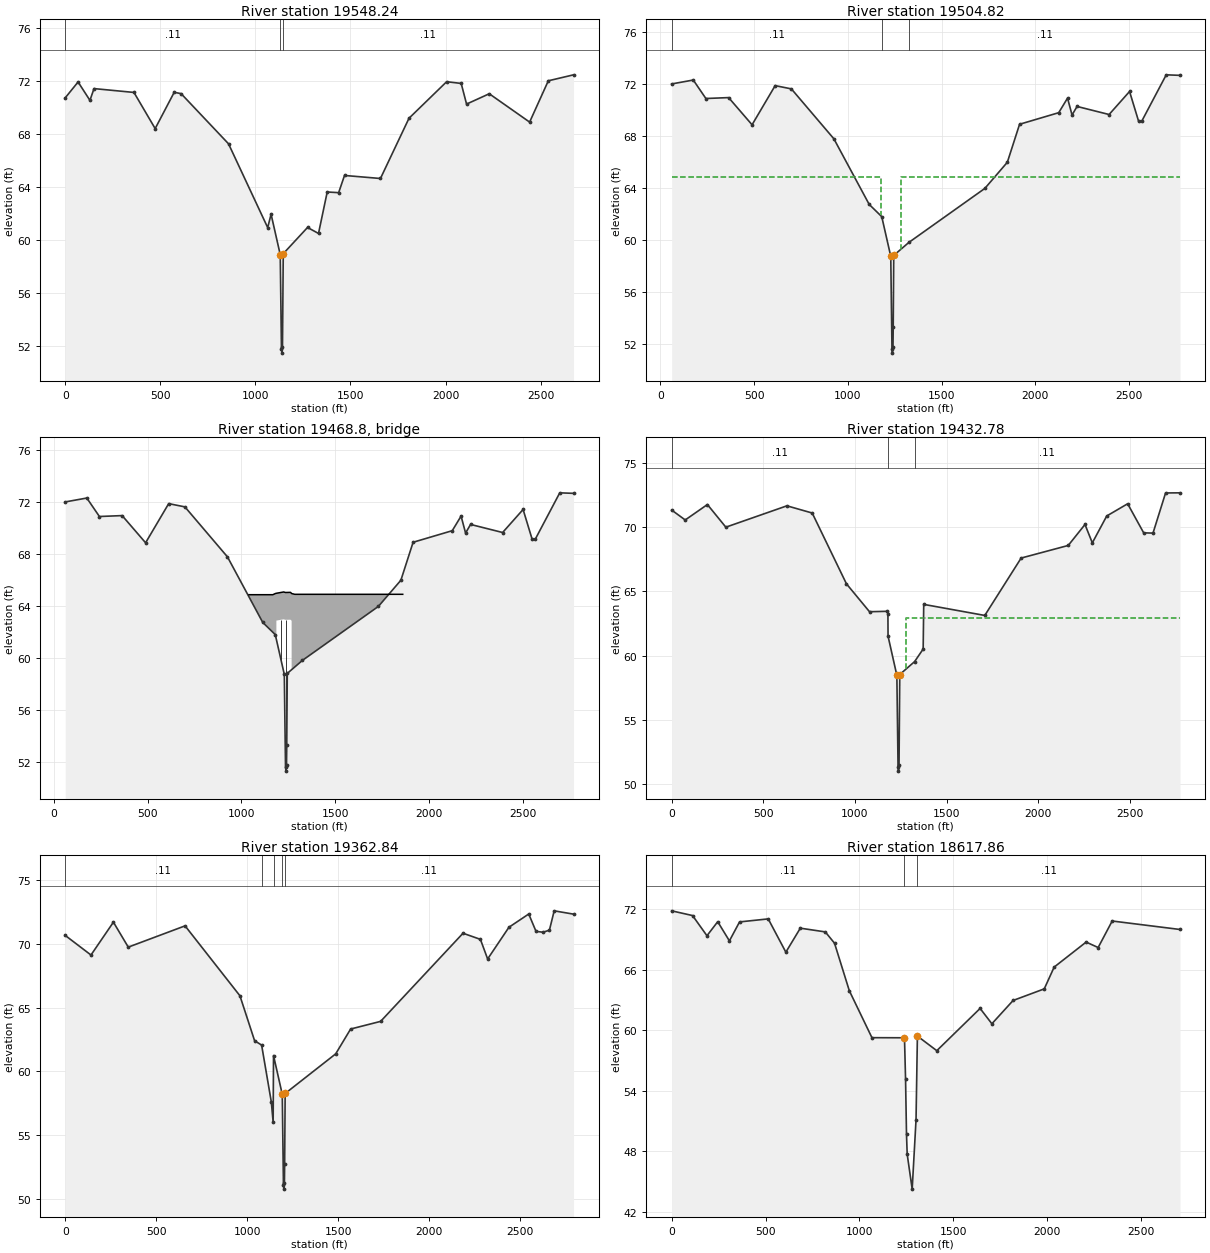
Type RM Length L Ch R = 1 ,19548.24,43.42,43.42,43.42
BEGIN DESCRIPTION:
Copy of 425s7u.   XS 4/4.
Notes: Adjusted elevations between CB's based on invert elevation of 425s7.
Bank Station offset =      3860
END DESCRIPTION:
XS GIS Cut Line= 5
     3171182.794     13952014.35     3170222.645    13951503.885
     3170045.935    13951441.709     3169299.613     13951302.13
      3168667.36     13951209.05
#Sta/Elev= 30
       0   70.76   67.68   71.96  130.05   70.57  151.47   71.46  361.53   71.17
  473.08   68.44  573.15   71.18  609.34   71.08  858.84   67.29 1064.79   60.96
 1082.63   61.97 1130.71   58.92 1137.21    51.8 1139.61   51.48 1142.52   51.94
 1146.59   58.99 1274.25   60.97 1331.99   60.52 1377.79   63.65 1437.93    63.6
 1468.76    64.9 1657.74   64.67 1807.86   69.22 2005.82   71.98 2082.31   71.85
 2110.56   70.29 2229.91   71.07 2442.18   68.93 2540.49   72.05 2673.07    72.5
#Mann= 3 , 0 , 0
       0     .11       0 1130.71     .06       0 1146.59     .11       0
Bank Sta=1130.71,1146.59
XS Rating Curve= 0
Exp/Cntr=.5,.3

Type RM Length L Ch R = 1 ,19504.82,72.04,72.04,72.04
BEGIN DESCRIPTION:
425s7u.  Surveyed section.  XS 3/4.
Bank Station offset =      3823
END DESCRIPTION:
XS GIS Cut Line= 6
     3171230.804    13951975.522     3170559.372    13951636.404
     3170229.903    13951461.242     3170053.193    13951399.066
     3169306.872    13951259.487     3168674.619    13951166.406
#Sta/Elev= 30
      60      72  175.21    72.3  242.43   70.88  363.66   70.95  488.75   68.86
  611.91   71.87  698.37   71.62  925.19   67.78 1113.42   62.74 1180.36    61.8
 1228.44   58.75 1234.94   51.63 1237.34   51.31 1240.25   51.77 1241.52    53.3
 1244.32   58.82 1325.09   59.82 1730.27   63.97 1850.17   65.98  1915.4    68.9
 2124.23   69.79 2171.27   70.91 2195.25   69.61 2221.97   70.27 2392.84   69.65
 2502.01   71.42 2550.31   69.13 2566.77   69.13 2697.58    72.7 2771.01   72.66
#Mann= 3 ,-1 , 0
      60     .11       0 1180.36     .06       0 1325.09     .11       0
#XS Ineff= 2 , 0
       0    1174   64.87    1281       0   64.87
Permanent Ineff=
       F       F
Bank Sta=1228.44,1244.32
XS Rating Curve= 0
Exp/Cntr=.5,.3

Type RM Length L Ch R = 3 ,19468.8 ,,,
BEGIN DESCRIPTION:
425s7: Tree Lane -(Conc. Bridge)
Notes: Extended bridge deck on LOB to x-sec sta 980 @  US & DS cross sections. Extended bridge deck on ROB to x-sec sta 1800 US and 1850 DS.
END DESCRIPTION:
Bridge Culvert--1,0,-1,-1, 0
Deck Dist Width WeirC Skew NumUp NumDn MinLoCord MaxHiCord MaxSubmerge Is_Ogee
19.02,34,2.6,0, 10, 10, 64.87, , .95, 0, 0,0,,
    1040 1167.37 1180.71 1186.23 1225.29 1234.67  1261.6 1267.59 1284.43    1860
   64.87   64.87   64.96   64.98   65.08   65.04   65.05   64.96    64.9    64.9
                           62.88   62.98   62.94   62.95   62.86
     980 1167.65 1180.99 1186.51 1225.57 1234.95 1261.88 1267.87 1284.71    1850
   64.87   64.87   64.96   64.98   65.08   65.04   65.05   64.96    64.9    64.9
                           62.88   62.98   62.94   62.95   62.86
Pier Skew, UpSta & Num, DnSta & Num=  ,1211.58, 4 ,1211.86, 4 , 3 , 3 , 0 ,,
    1.35    1.35     2.2     2.2
      50   60.72   60.72   62.92
    1.35    1.35     2.2     2.2
      50   60.72   60.72   62.92
Pier Skew, UpSta & Num, DnSta & Num=  ,1237.07, 4 ,1237.35, 4 , 3 , 3 , 0 ,,
    1.35    1.35     2.2     2.2
      50   60.72   60.72   62.92
    1.35    1.35     2.2     2.2
      50   60.72   60.72   62.92
BR Coef=-1 , 0 , 0 ,, 0 ,,,.8,0,,0,
WSPro=,,,, 1 ,,,, 0 ,,,, 0 ,,,,-1 ,-1 ,-1 , 0 , 0 , 0 , 0 , 0
BC Design=,, 0 ,, 0 ,,,,,,

Type RM Length L Ch R = 1 ,19432.78,69.94,69.94,69.94
BEGIN DESCRIPTION:
Copy of 425s7u.   XS 2/4.
Notes:  Adjusted elevations between CB's based on invert elevation of 425s7.
Bank Station offset =      3762
END DESCRIPTION:
XS GIS Cut Line= 6
     3171339.744    13951866.582     3170579.378    13951566.721
     3170252.132     13951392.74     3170075.422    13951330.564
     3169329.101    13951190.985     3168696.848    13951097.905
#Sta/Elev= 30
       0   71.32   73.87   70.55  194.92   71.75  295.56   69.99  628.91   71.65
  766.82   71.09  953.53   65.59 1079.44   63.42  1173.5   63.45 1179.92   63.28
 1180.64   61.52 1228.72   58.47 1235.22   51.35 1237.62   51.03 1240.53   51.49
  1244.6   58.54 1325.37   59.54 1372.26   60.52 1375.31   63.99 1708.44   63.13
 1906.85   67.59 2163.86   68.57 2255.26    70.2 2295.24   68.77 2373.86   70.86
 2487.97   71.81 2575.41   69.55 2626.37   69.53 2694.96   72.65 2773.64   72.66
#Mann= 3 ,-1 , 0
       0     .11       0 1180.64     .06       0 1325.37     .11       0
#XS Ineff= 2 , 0
       0 1176.29   62.94    1279       0   62.94
Permanent Ineff=
       F       F
Bank Sta=1228.72,1244.6
XS Rating Curve= 0
Exp/Cntr=.5,.3

Type RM Length L Ch R = 1 ,19362.84,648.23,744.97,699.27
BEGIN DESCRIPTION:
Copy of 425s7u.   XS 1/4.
Notes: Adjusted elevations between CB's based on invert elevation of 425s7. Added special ineffective "n" value in small side ditch
Bank Station offset =      3798
END DESCRIPTION:
XS GIS Cut Line= 6
     3171370.869    13951796.549     3170579.631    13951496.212
     3170291.146    13951342.838     3170114.436    13951280.663
     3169368.115    13951141.083     3168701.838     13951041.75
#Sta/Elev= 30
       0   70.68   141.6   69.14  264.89   71.72  346.51   69.76  658.68   71.43
   960.1   65.94 1040.74   62.41  1079.3   62.07 1132.55   57.61 1142.67   56.01
 1144.65   61.25 1192.73    58.2 1199.23   51.08 1201.63   50.76 1204.54   51.22
 1205.81   52.75 1208.61   58.27 1486.34   61.38 1568.35   63.33  1733.2   63.93
    2186   70.85 2281.55   70.37 2321.28   68.83 2438.36   71.32  2547.1   72.36
 2587.07      71 2625.34   70.93  2660.7   71.09 2686.96   72.61 2793.27   72.35
#Mann= 5 ,-1 , 0
       0     .11       0  1079.3     .99       0 1144.65     .11       0
 1192.73     .06       0 1208.61     .11       0
Bank Sta=1192.73,1208.61
XS Rating Curve= 0
Exp/Cntr=.3,.1

Type RM Length L Ch R = 1 ,18617.86,799.66,1133.88,1248.05
BEGIN DESCRIPTION:
425v9
Bank Station offset =      3719
END DESCRIPTION:
XS GIS Cut Line= 4
     3171497.696    13951528.339     3170557.144    13950757.674
     3170409.886    13950702.043     3169280.856    13949990.124
#Sta/Elev= 30
       0   71.82   111.3   71.35  187.96   69.35  245.29   70.74   307.6   68.84
  361.64   70.72  514.37   71.02  608.31   67.72  685.36    70.1   818.4   69.73
  867.58   68.61  946.34    63.9 1066.93   59.24 1240.32   59.23 1246.02   55.13
 1251.05   49.66  1254.7   47.69 1281.31   44.22 1301.82   51.09 1309.14    59.4
 1412.46   57.95  1643.2   62.14 1705.91   60.62 1818.98   62.93 1984.93   64.08
 2037.72   66.24 2208.01   68.72 2272.11   68.18 2346.88   70.81 2708.12   69.97
#Mann= 3 ,-1 , 0
       0     .11       0 1240.32     .06       0 1309.14     .11       0
Bank Sta=1240.32,1309.14
XS Rating Curve= 0
Exp/Cntr=.3,.1

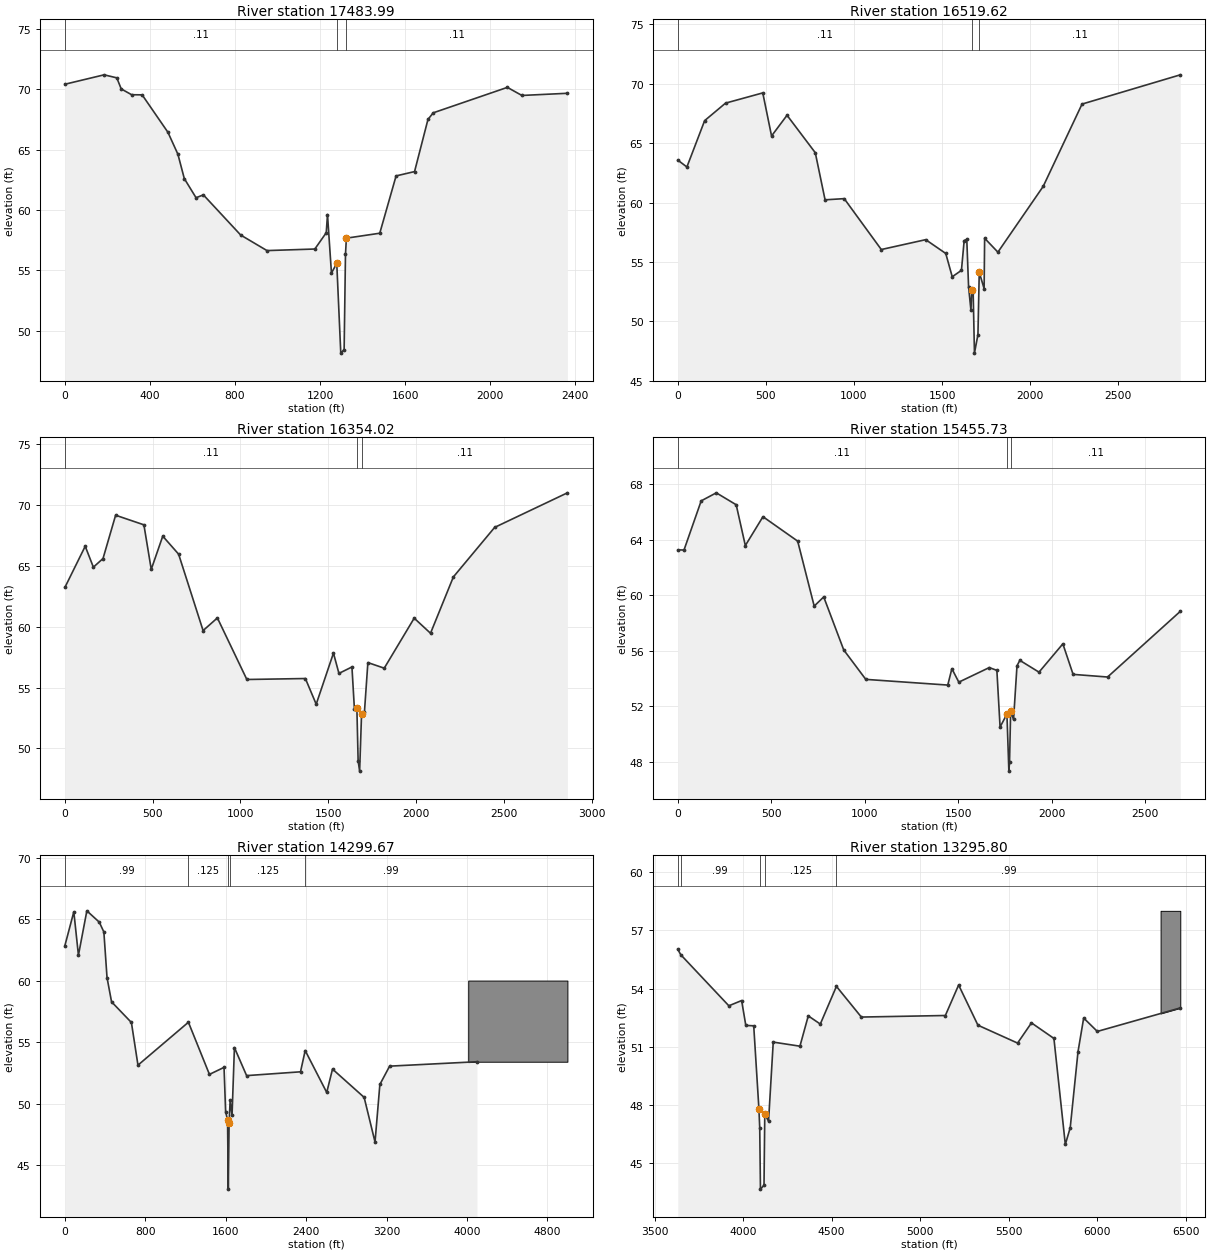
Type RM Length L Ch R = 1 ,17483.99,1120.04,964.36,796.84
BEGIN DESCRIPTION:
425v10
Bank Station offset =      3700
END DESCRIPTION:
XS GIS Cut Line= 6
     3171660.565    13951410.711     3171162.539    13950230.816
     3171126.543    13950132.644     3171126.714      13949854.4
     3170927.651    13949447.225     3170810.023    13949230.065
#Sta/Elev= 30
       0   70.43  184.29   71.21  244.04   70.96  264.91   70.04  313.94   69.56
  363.28   69.55  484.46   66.45  531.44   64.63  561.59   62.61  616.89   61.02
  651.23   61.26  826.76   57.93  950.48   56.64 1175.59   56.77 1229.25   58.12
 1235.13   59.63 1253.72   54.78 1278.76   55.58 1297.63   48.14 1313.42   48.44
 1319.75   56.33 1324.03   57.67 1481.01   58.08 1557.77   62.83 1644.68   63.19
 1707.71   67.51 1732.43   68.06 2081.25   70.17 2149.59    69.5  2363.7   69.68
#Mann= 3 , 0 , 0
       0     .11       0 1278.76     .06       0 1324.03     .11       0
Bank Sta=1278.76,1324.03
XS Rating Curve= 0
Exp/Cntr=.3,.1

Type RM Length L Ch R = 1 ,16519.62,165.6,165.6,165.6
BEGIN DESCRIPTION:
425v11
Bank Station offset =      3316
END DESCRIPTION:
XS GIS Cut Line= 5
     3173207.828    13950704.942     3172631.973    13950118.719
     3171921.738    13949726.865     3171823.566    13949681.052
       3170936.7    13949012.906
#Sta/Elev= 30
       0   63.57   51.68   62.99  152.46   66.89  270.94   68.36  482.27   69.22
   532.1    65.6  619.93   67.34   780.3   64.19  835.78   60.23  944.45   60.33
 1154.86   56.05 1406.83   56.88 1520.68   55.72 1557.46   53.76 1609.67    54.3
 1625.17    56.8    1640   56.91 1650.19   52.91 1663.66   50.93  1668.2   52.65
  1676.2   52.47 1683.54   47.34 1703.29   48.89 1710.76   54.14 1738.41   52.76
 1741.24      57 1816.59   55.83 2073.63   61.36 2294.05   68.28 2851.63   70.74
#Mann= 3 , 0 , 0
       0     .11       0  1668.2     .06       0 1710.76     .11       0
Bank Sta=1668.2,1710.76
XS Rating Curve= 0
Exp/Cntr=.3,.1

Type RM Length L Ch R = 1 ,16354.02,708.33,898.29,998.46
BEGIN DESCRIPTION:
425v12
Channel transitions to maintained channel just u/s of this section.
Bank Station offset =      3321
END DESCRIPTION:
XS GIS Cut Line= 5
     3173216.877    13950623.507     3172715.545    13950007.324
        3172033.    13949595.969      3171869.38    13949520.704
     3171009.086    13948850.036
#Sta/Elev= 30
       0   63.24  115.61   66.62  162.06    64.9     217   65.61  288.81   69.17
  449.91   68.38  491.72   64.72   557.3   67.45  647.58   65.97  787.02   59.69
  868.49   60.73 1036.31   55.67 1369.65   55.75 1431.32   53.64 1529.62   57.84
 1560.84   56.17 1634.91    56.7 1649.09   53.21 1662.94   53.35 1670.13   48.99
 1678.67   48.14 1689.56    52.8 1706.08      53 1725.65   57.06 1818.86    56.6
 1989.49   60.71 2082.42   59.47 2212.66    64.1 2447.78   68.17 2862.21   71.01
#Mann= 3 , 0 , 0
       0     .11       0 1662.94     .06       0 1689.56     .11       0
Bank Sta=1662.94,1689.56
XS Rating Curve= 0
Exp/Cntr=.3,.1

Type RM Length L Ch R = 1 ,15455.73,954.92,1156.06,1329.29
BEGIN DESCRIPTION:
425v13
Bank Station offset =      3229
END DESCRIPTION:
XS GIS Cut Line= 5
     3173271.167    13950505.879     3172967.708    13949899.117
      3172550.04    13949003.663     3172474.775    13948866.222
     3172055.907    13948110.296
#Sta/Elev= 30
       0   63.28   33.26   63.27  125.12   66.81  205.98   67.39  312.38   66.53
  361.23   63.59  455.51   65.67  641.15   63.91  729.52   59.23  780.42   59.89
  887.52   56.07 1005.42   53.95 1443.85   53.54 1465.84   54.72 1502.85   53.75
 1665.74    54.8 1706.45    54.6 1723.61   50.52 1760.25   51.45 1770.66   47.34
 1774.18   47.99 1780.16   51.67 1795.64   51.06  1814.1   54.93 1829.31   55.32
 1931.83   54.47 2059.34   56.51 2114.16   54.31 2298.48   54.12  2687.4   58.85
#Mann= 3 ,-1 , 0
       0     .11       0 1760.25     .06       0 1780.16     .11       0
Bank Sta=1760.25,1780.16
XS Rating Curve= 0
Exp/Cntr=.3,.1

Type RM Length L Ch R = 1 ,14299.67,1211.3,1003.88,599.81
BEGIN DESCRIPTION:
425v14
 Extended cross-section on ROB.
Bank Station offset =      3374
END DESCRIPTION:
XS GIS Cut Line= 6
     3173325.457    13950406.347     3173350.041    13949883.608
     3173548.124    13948849.859     3173597.211     13948741.87
     3173613.928    13948119.275     3173090.822    13946415.118
#Sta/Elev= 30
       0   62.85   88.64   65.59  134.49   62.06  218.29   65.67   341.8   64.75
  387.54   63.95  419.01   60.24  464.06   58.27   661.6   56.59  726.88   53.12
 1228.78   56.61 1438.03   52.37 1583.36   52.94 1599.04   49.34 1618.29   48.67
 1625.67   43.04 1633.58   48.44 1644.12   50.26 1662.92   49.03 1686.65   54.55
 1807.86   52.27  2344.3   52.58 2390.72   54.31 2605.13    50.9  2662.6    52.8
 2977.47    50.5 3085.73   46.87 3133.84   51.55 3230.92   53.04    4100    53.4
#Mann= 5 ,-1 , 0
       0     .99       0 1228.78    .125       0 1618.29     .07       0
 1644.12    .125       0 2390.72     .99       0
#Block Obstruct= 1 ,-1
    4013    5000      60
Bank Sta=1618.29,1633.58
XS Rating Curve= 0
Exp/Cntr=.3,.1

Type RM Length L Ch R = 1 ,13295.80,45.82,45.82,45.82
BEGIN DESCRIPTION:
425s6u.  Surveyed section.  XS 4/4.
Notes: Extended cross-section on LOB & ROB.
Bank Station offset =      3394
END DESCRIPTION:
XS GIS Cut Line= 6
        3174760.       13948970.     3174522.565    13948775.639
     3174329.587     13948669.12     3174058.569    13948439.059
     3173605.955    13947764.237     3173335.377     13947149.15
#Sta/Elev= 30
 3631.39   56.02 3648.09   55.74 3919.88   53.11 3992.06   53.38 4015.68    52.1
 4060.39   52.08 4089.69   47.81 4094.32   46.82 4098.41   43.67  4118.5   43.87
 4122.84   47.52 4144.18   47.17 4170.66   51.24 4321.47   51.03 4368.57   52.59
 4436.52   52.17 4527.63   54.11 4668.42   52.53 5143.07   52.61 5218.04   54.18
 5327.17   52.11  5551.1   51.19 5629.53   52.23 5756.37   51.43 5820.83   45.97
 5848.48   46.83 5892.44   50.74  5924.5   52.48 6001.66   51.79 6470.36      53
#Mann= 5 ,-1 , 0
 3631.39    .125       0 3648.09     .99       0 4094.32     .04       0
 4122.84    .125       0 4527.63     .99       0
#Block Obstruct= 1 ,-1
    6359 6470.36      58
Bank Sta=4089.69,4122.84
XS Rating Curve= 0
Exp/Cntr=.5,.3