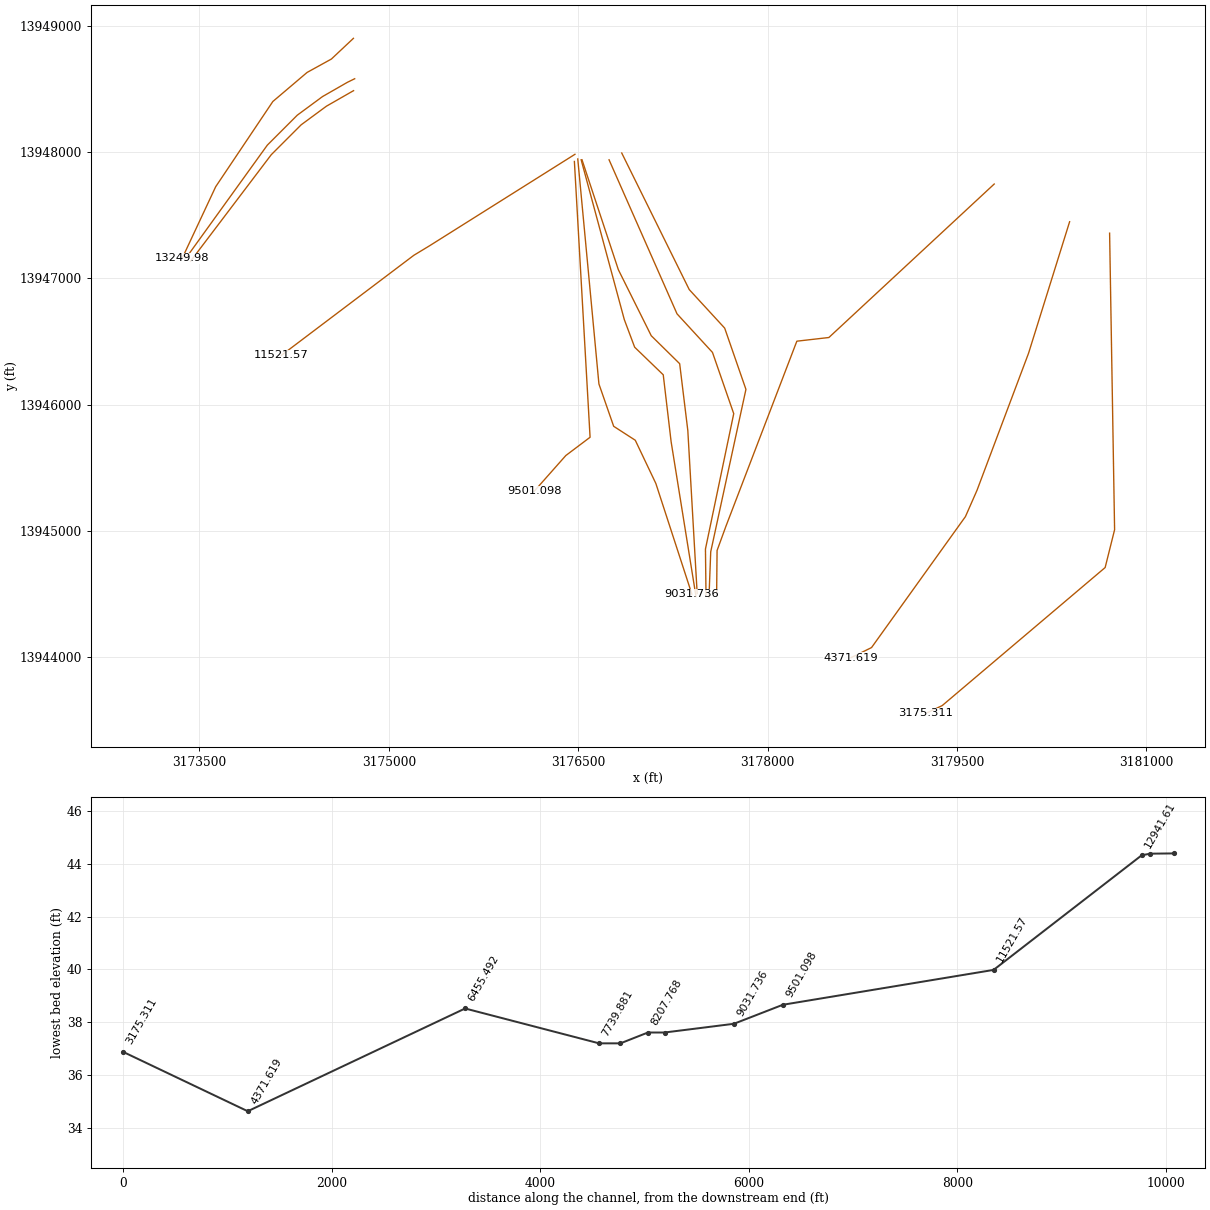
HEC-RAS study G103-33-00.prj: G103-33-00

--- G103-33-00.g02 (geometry) --- (continued)

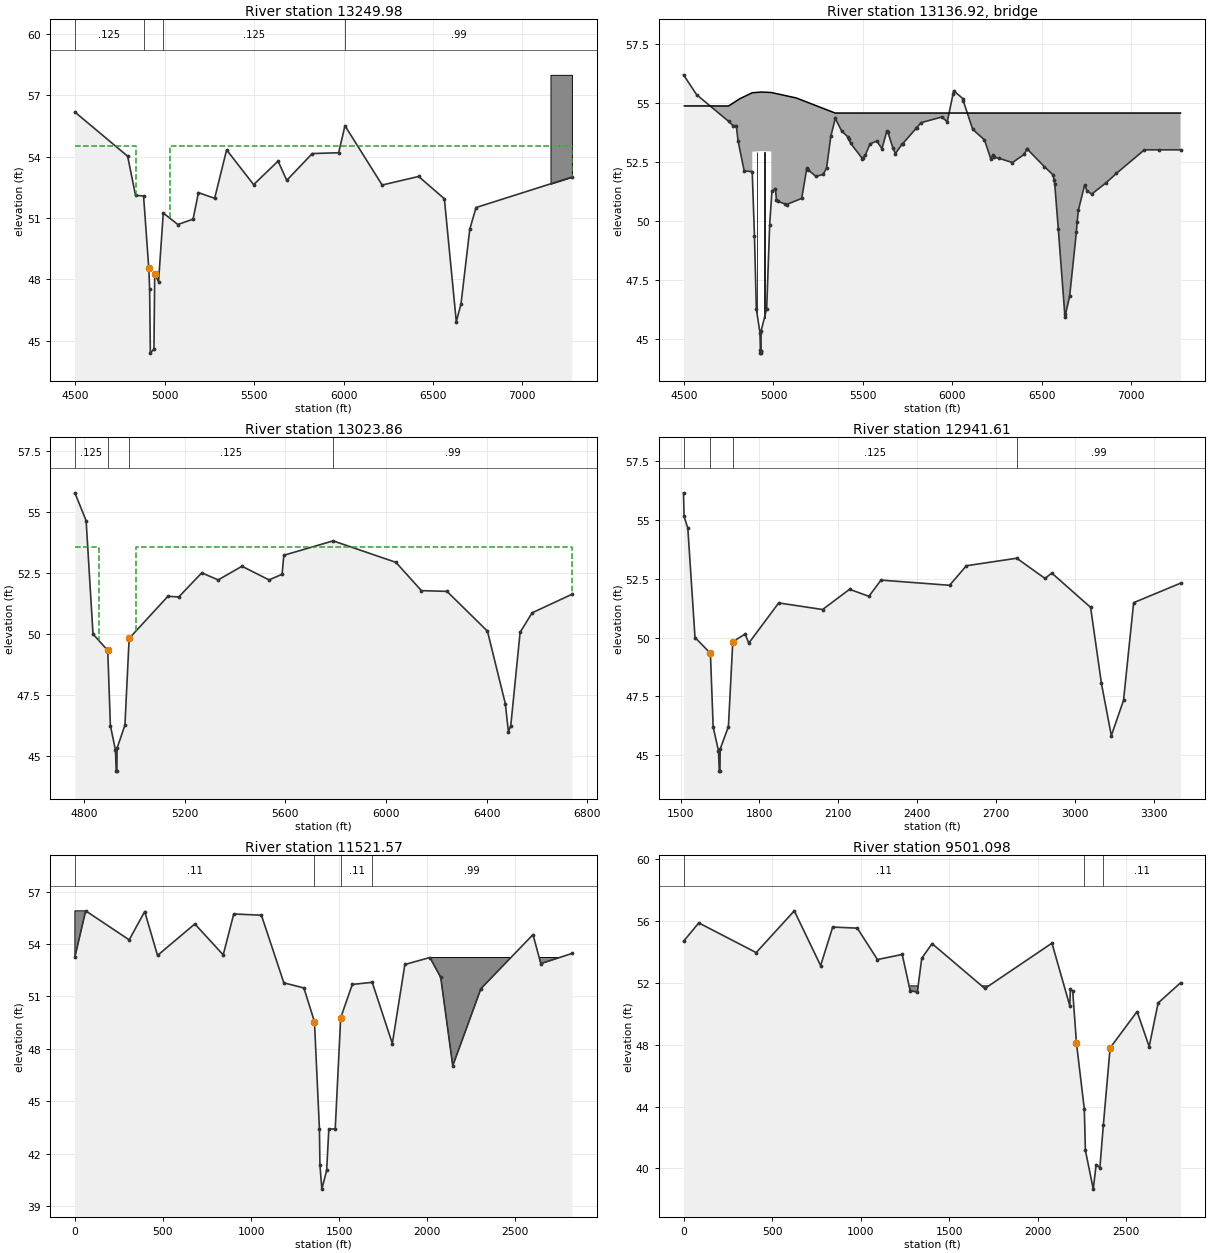
Type RM Length L Ch R = 1 ,13249.98,226.11,226.11,226.11
BEGIN DESCRIPTION:
Copy of 425s6u.   XS 3/4.
Notes: Adjusted elevations between CB's based on invert elevation of 425s5. Extended cross-section on LOB & ROB.
Bank Station offset =      3404
ineffective stations widened to reduce Vel. Head (checkRAS comments avoided)
END DESCRIPTION:
XS GIS Cut Line= 6
        3174720.       13948900.     3174545.762    13948736.247
     3174352.785    13948629.728     3174081.767    13948399.667
     3173629.153    13947724.845     3173364.193    13947158.755
#Sta/Elev= 30
 4497.13   56.18 4792.14   54.02 4836.47    52.1 4881.18   52.08 4910.48   48.53
 4915.11   47.54  4919.2   44.39 4939.29   44.59 4943.63   48.24 4964.97   47.89
 4991.45   51.24 5073.05   50.68 5158.06   50.94 5188.25   52.24  5278.8   51.96
 5345.69   54.33 5496.89   52.63 5633.52   53.78 5682.04   52.84 5824.66   54.15
 5972.25   54.19 6007.63   55.51 6215.67   52.61 6419.61   53.03 6563.52   51.94
 6630.27   45.93  6656.5   46.79 6705.74   50.45 6740.63   51.51 7276.92      53
#Mann= 4 ,-1 , 0
 4497.13    .125       0 4881.18     .04       0 4991.45    .125       0
 6007.63     .99       0
#XS Ineff= 2 , 0
       0    4840    54.5    5030       0    54.5
Permanent Ineff=
       F       F
#Block Obstruct= 3 ,-1
                                                 7157.01 7276.92      58
Bank Sta=4910.48,4943.63
XS Rating Curve= 0
Exp/Cntr=.5,.3

Type RM Length L Ch R = 3 ,13136.92,,,
BEGIN DESCRIPTION:
Kingwood Drive Westbound, Eastbound, and Footbridge 425s4, 425s5, & 425s6:
425s4-(Kingswood Dr. Eastbound Conc. Bridge)
425s5-(Kingswood Dr. Westbound Conc. Bridge)
425s6-(Foot Bridge)
Notes: Extended bridge deck on LOB to x-sec sta 0 @  US & DS cross sections. Extended bridge deck on ROB to x-sec sta 3536.52 US and 3446.6 DS.
END DESCRIPTION:
Bridge Culvert--1,0,-1,-1, 0
Deck Dist Width WeirC Skew NumUp NumDn MinLoCord MaxHiCord MaxSubmerge Is_Ogee
28.06,170,2.6,0, 11, 9, 54.56, , .95, 0, 0,0,,
    4502 4749.09 4812.51  4881.6 4881.62 4933.52 4987.97    4988 5127.17  5344.8
 7276.92
   54.86   54.86   55.17   55.42   55.42   55.45   55.43   55.43    55.2   54.56
   54.56
                                   52.92   52.95   52.93
        
 4723.15  4881.7 4881.72 4936.98 4988.61 4988.65  5047.4 5305.55  6738.6
   54.64   55.41   55.41   55.45   55.33   55.33   55.26   54.36   54.36
                   52.91   52.95   52.83
Pier Skew, UpSta & Num, DnSta & Num=  ,4908.46, 4 ,4915.71, 4 , 3 , 3 , 0 ,,
    1.35    1.35       2       2
      43   49.92   49.92   52.92
    1.35    1.35       2       2
      43    50.3    50.3    53.3
Pier Skew, UpSta & Num, DnSta & Num=  ,4949.34, 4 ,4956.1, 4 , 3 , 3 , 0 ,,
    1.35    1.35       2       2
      43   49.92   49.92   52.92
    1.35    1.35       2       2
      43    50.3    50.3    53.3
BR Coef=-1 , 0 , 0 ,, 0 ,,,.31,0,,0,
WSPro=,,,, 1 ,,,, 0 ,,,, 0 ,,,,-1 ,-1 ,-1 , 0 , 0 , 0 , 0 , 0
BR U #Sta/Elev= 88
 4497.13   56.18 4569.96   55.34  4748.6   54.21 4772.91   54.03 4792.14   54.02
 4802.15   53.37 4836.47    52.1 4881.18   52.08 4893.84   49.33 4904.33   46.25
 4924.44   45.25 4927.53   44.38 4927.54   44.51 4927.65   44.45 4930.07   44.45
 4930.11   44.38 4930.94   45.32 4962.22   46.27 4978.87   49.82 4991.45   51.24
 5010.87   51.36 5016.76   50.87 5023.09   50.82  5066.4    50.7 5073.05   50.68
 5158.06   50.94 5185.61   52.17 5188.25   52.24    5193   52.16 5237.65   51.87
  5278.8   51.96 5297.34   52.24 5320.82   53.57 5345.69   54.33 5381.98   53.79
 5414.75   53.56  5421.9   53.44 5432.44   53.27 5496.89   52.63 5498.22   52.65
 5513.57   52.77  5540.2   53.25 5577.49   53.37  5607.1   53.05 5633.52   53.78
 5638.91   53.77 5668.37   53.07 5682.04   52.84  5719.7   53.24    5723   53.26
 5799.25   53.92 5801.91   53.94 5824.66   54.15 5941.37   54.39 5972.25   54.19
 6004.26   55.36 6007.63   55.51 6059.05   55.17  6062.5   55.06 6114.15   53.87
 6180.35   53.42 6215.67   52.61 6226.17   52.76 6235.17   52.69 6261.57   52.64
  6336.8   52.46  6403.1   52.81 6416.85   53.03 6419.61   53.03 6515.88   52.28
 6563.52   51.94 6569.49   51.72 6573.35   51.53 6593.05   49.64 6630.27   45.93
 6633.24   46.02  6656.5   46.79 6694.59   49.53 6698.32   49.93 6705.74   50.45
 6740.63   51.51 6752.79   51.27 6779.45   51.12  6860.2    51.6 6917.96      52
  7074.9      53 7157.01      53 7276.92      53
BR U #Mann= 4
 4497.13    .125 4881.18     .04 4991.45    .125 6007.63     .99
BR U Banks=4893.84,4978.87
BC Design=,, 0 ,, 0 ,,,,,,

Type RM Length L Ch R = 1 ,13023.86,82.25,82.25,82.25
BEGIN DESCRIPTION:
425s4d.  Surveyed section.  XS 2/4.
Notes: Inserted Blocked Obstruction. Increased Manning's "n" for main channel due to 425s6---(9-1.0ft pier groups)
Bank Station offset =      3336
ineffective stations widened to reduce Vel. Head (checkRAS comments avoided)
END DESCRIPTION:
XS GIS Cut Line= 6
        3174730.       13948580.     3174672.608     13948551.89
     3174475.182    13948438.699     3174275.124    13948291.288
     3174038.213    13948054.377     3173393.008    13947158.755
#Sta/Elev= 30
  4763.3   55.79 4807.97   54.65 4835.29      50 4893.84   49.33 4904.33   46.25
 4924.44   45.25 4927.53   44.38 4930.11   44.38 4930.94   45.32 4962.22   46.27
 4978.87   49.82 5133.15   51.55 5175.94   51.52 5267.49   52.51 5332.84   52.22
 5427.36   52.78  5534.9   52.22 5586.77   52.45 5593.63   53.23 5789.55   53.82
 6039.15   52.94 6140.39   51.78    6242   51.75 6402.87   50.12 6473.86   47.15
 6486.29   45.99  6495.7   46.25 6532.67   50.07 6580.35   50.87  6738.6   51.63
#Mann= 4 ,-1 , 0
  4763.3    .125       0 4893.84     .04       0 4978.87    .125       0
 5789.55     .99       0
#XS Ineff= 2 , 0
       0    4860   53.55    5005       0   53.55
Permanent Ineff=
       F       F
#Block Obstruct= 2 , 0
  3263.6                  6710.2  3263.6      58
Bank Sta=4893.84,4978.87
XS Rating Curve= 0
Exp/Cntr=.5,.3

Type RM Length L Ch R = 1 ,12941.61,1387.74,1420.03,1377.79
BEGIN DESCRIPTION:
Copy of 425s4d.   XS 1/4.
Notes: Adjusted elevations between CB's based on invert elevation of 425s4. Inserted Blocked Obstruction
Special ineffective flow was used to reflect a drainage ditch
Bank Station offset =      3353
END DESCRIPTION:
XS GIS Cut Line= 6
 3174721.062410613948485.3954184      3174703.38    13948475.612
     3174505.954    13948362.421     3174305.896    13948215.009
     3174068.985    13947978.098 3173430.599742813947135.3759051
#Sta/Elev= 30
 1511.45   56.15 1513.28   55.15 1527.69   54.65 1555.01      50 1613.56   49.33
 1624.05   46.19 1644.16   45.19 1647.25   44.32 1649.83   44.32 1650.66   45.26
 1681.94   46.21 1698.59   49.82 1745.63   50.15 1759.23   49.76 1873.02   51.47
 2039.89   51.19 2142.31   52.05 2215.66   51.75 2261.77   52.44 2522.42   52.22
 2586.08   53.05 2777.53   53.37 2884.98   52.51 2910.65   52.74 3058.23   51.28
 3099.25   48.05 3136.95   45.83 3183.27   47.33  3221.7   51.48    3400   52.31
#Mann= 4 ,-1 , 0
 1511.45    .125       0 1613.56     .04       0 1698.59    .125       0
 2777.53     .99       0
#Block Obstruct= 2 , 0
       0                 3382.72       0      56
Bank Sta=1613.56,1698.59
XS Rating Curve= 0
Exp/Cntr=.3,.1

Type RM Length L Ch R = 1 ,11521.57,2020.48,2020.48,2020.48
BEGIN DESCRIPTION:
425v15
Notes: Inserted Blocked Obstructionin the ROB to reflect the presence of a pond on a golf course. Added special ineffective "n" value to the ROB because this area reflects a golf course fairway.
Block in LOB to prevent flow in a non-conveying area
Bank Station offset =      3598
END DESCRIPTION:
XS GIS Cut Line= 4
     3176474.273    13947981.397     3175325.742    13947258.894
     3175198.342    13947181.651     3174148.854    13946388.892
#Sta/Elev= 30
       0   53.26   61.21    55.9  308.24   54.24  396.24   55.86  469.09   53.35
  680.86   55.15  841.85   53.38   901.7   55.72 1058.65   55.65 1186.13   51.78
 1299.63   51.49 1359.78   49.56 1388.01   43.42 1390.81   41.37  1401.8   39.98
 1429.06   41.06 1441.28   43.41 1477.74   43.43 1508.63   49.78 1574.59   51.69
 1687.63   51.81 1801.83   48.31    1873   52.83  2015.1   53.23 2076.57   52.09
 2144.73   47.03 2304.73   51.45 2600.18   54.54 2644.74   52.88 2821.12   53.46
#Mann= 4 ,-1 , 0
       0     .11       0 1359.78     .04       0 1508.63     .11       0
 1687.63     .99       0
#Block Obstruct= 2 ,-1
       0   61.89    55.9  2015.1 2821.12   53.23
Bank Sta=1359.78,1508.63
XS Rating Curve= 0
Exp/Cntr=.3,.1

Type RM Length L Ch R = 1 ,9501.098,287.23,469.36,676.35
BEGIN DESCRIPTION:
425v16
Notes: Extended cross-section on ROB.
Bank Station offset =      2686
END DESCRIPTION:
XS GIS Cut Line= 5
     3176470.004    13947924.661      3176594.22    13945740.546
     3176402.058    13945595.767     3176215.012    13945384.646
 3176151.0521057 13945312.453722
#Sta/Elev= 30
       0   54.68   86.04   55.87  410.19   53.95  625.39   56.65   774.1   53.11
  842.25    55.6   981.2   55.53 1095.07    53.5  1234.8   53.83 1279.96   51.48
 1320.33    51.4 1345.17   53.58 1403.51   54.53 1701.56   51.63 2080.34   54.56
 2181.36   50.51 2184.44   51.62 2197.76   51.44 2219.05   48.08  2263.1   43.85
 2269.38   41.16 2313.85   38.66 2330.01   40.25 2351.11   40.04  2370.5   42.78
 2408.96   47.79 2561.34   50.14 2629.52   47.87 2679.81   50.69 2806.75      52
#Mann= 3 ,-1 , 0
       0     .11       0  2263.1     .04       0  2370.5     .11       0
#Block Obstruct= 1 ,-1
    1250    1825    51.8
Bank Sta=2219.05,2408.96
XS Rating Curve= 0
Exp/Cntr=.3,.1

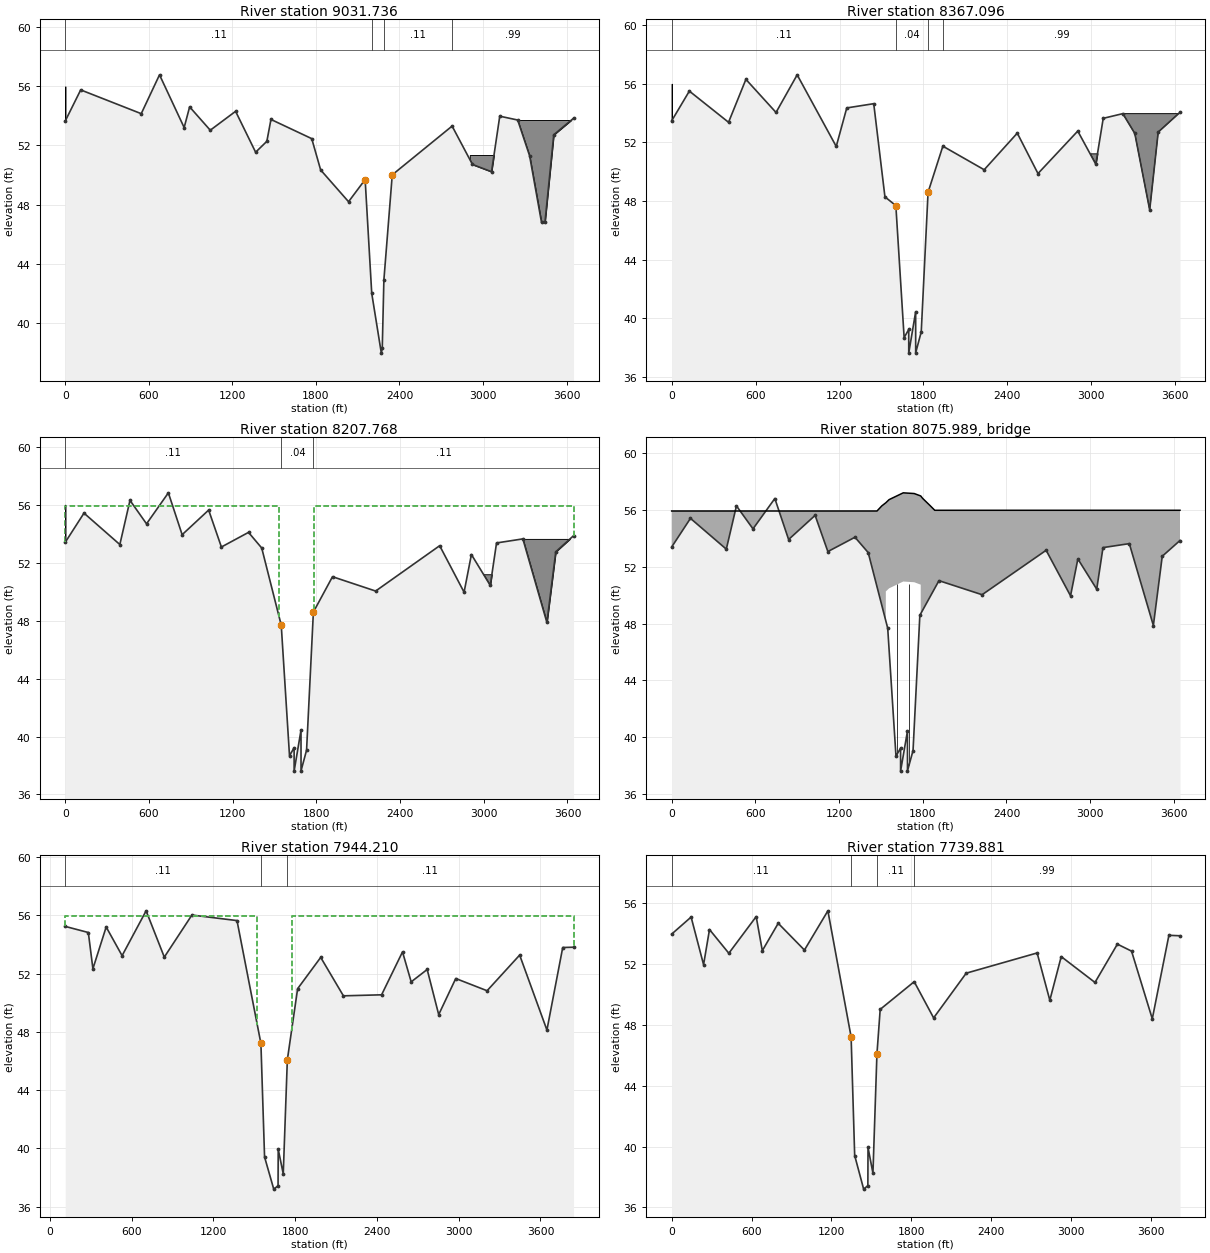
Type RM Length L Ch R = 1 ,9031.736,664.64,664.64,601.7
BEGIN DESCRIPTION:
425s3u
Notes: Inserted Blocked Obstructions for areas not considered the conveyance area
Pipeline is judged too small to impact and is not included in model based on PMT criterion.
Bank Station offset =      2730
END DESCRIPTION:
XS GIS Cut Line= 6
     3176496.793    13947944.753     3176664.288    13946162.684
     3176781.116    13945827.413     3176952.218    13945716.855
     3177115.095    13945374.755     3177400.513    13944497.869
#Sta/Elev= 30
       0   53.65  111.26   55.76   545.9   54.15  677.12   56.78  854.03   53.21
  893.34   54.61 1041.47   53.03 1223.38   54.31  1367.2   51.54 1447.85   52.28
 1477.26   53.76 1770.08   52.46  1834.1   50.34 2034.36   48.19 2153.51   49.69
 2200.79   41.99 2269.77   37.94 2276.43   38.28 2288.06   42.89 2348.19   50.01
  2777.9   53.31 2924.18   50.71 3061.01   50.22 3119.99   53.98 3248.78   53.72
 3334.32    51.3 3419.96   46.79 3444.74   46.81 3507.84   52.72 3649.74   53.84
#Mann= 4 ,-1 , 0
       0     .11       0 2200.79     .04       0 2288.06     .11       0
  2777.9     .99       0
#Block Obstruct= 3 ,-1
       0       1      56    2905    3090   51.35    3248    4000   53.72
Bank Sta=2153.51,2348.19
XS Rating Curve= 0
Exp/Cntr=.3,.1

Type RM Length L Ch R = 1 ,8367.096,159.33,159.33,159.33
BEGIN DESCRIPTION:
Copy of 425s2u.  XS 4/4.
Notes:  Inserted Blocked Obstruction not considered conveyance area
Bank Station offset =      3305
END DESCRIPTION:
XS GIS Cut Line= 6
     3176523.582    13947938.055     3176865.218    13946672.833
     3176947.345    13946453.738     3177173.727    13946235.254
     3177236.199    13945704.662     3177433.172    13944479.207
#Sta/Elev= 30
       0   53.47  126.37    55.5  406.65   53.37  530.73    56.3  746.19   54.04
  897.33   56.61 1176.67   51.72 1251.92   54.35 1444.75   54.64 1524.85   48.28
 1602.86   47.68  1662.1   38.67 1695.13   39.23 1695.17   37.61 1744.53   40.44
 1744.68   37.63 1784.43   39.06 1833.22   48.59 1939.05   51.74 2234.51   50.13
 2471.25   52.63 2619.15   49.87 2903.57   52.77 3032.46   50.51  3085.7   53.64
 3225.72   53.96 3311.41   52.61 3417.93   47.39 3478.79    52.7 3634.61   54.05
#Mann= 4 ,-1 , 0
       0     .11       0 1602.86     .04       0 1833.22     .11       0
 1939.05     .99       0
#Block Obstruct= 3 ,-1
       0       1      56    2910    3075   51.25    3225    4000   53.96
Bank Sta=1602.86,1833.22
XS Rating Curve= 0
Exp/Cntr=.5,.3

Type RM Length L Ch R = 1 ,8207.768,263.56,263.56,263.56
BEGIN DESCRIPTION:
425s2u.  Surveyed section.  XS 3/4.
Notes:  Inserted Blocked Obstruction  not considered conveyance area
Bank Station offset =      3359
END DESCRIPTION:
XS GIS Cut Line= 6
     3176530.279    13947938.055     3176818.261    13947067.412
     3177078.614    13946544.817     3177303.787    13946323.259
     3177368.369    13945793.488     3177442.504    13944502.535
#Sta/Elev= 30
       0    53.4  134.65   55.42  391.67   53.25  464.37    56.3  582.95   54.68
  739.46   56.82   838.2   53.93 1028.23   55.63 1119.61   53.08 1313.97   54.09
  1408.7   53.01 1548.61   47.68 1607.85   38.67 1640.88   39.23 1640.92   37.61
 1690.28   40.44 1690.43   37.63 1730.18   39.06 1778.97   48.59 1916.02   51.03
 2225.17   50.04 2684.19   53.17 2859.15   49.96  2911.7   52.56 3046.83   50.43
 3091.87   53.36 3280.48   53.64 3452.88   47.87 3516.58   52.75 3643.78   53.86
#Mann= 3 , 0 , 0
       0     .11       0 1548.61     .04       0 1778.97     .11       0
#XS Ineff= 2 , 0
       0  1533.6   55.94 1785.71       0   55.94
Permanent Ineff=
       F       F
#Block Obstruct= 3 ,-1
       0       1      56    2990    3070    51.2 3280.48    4000   53.64
Bank Sta=1548.61,1778.97
XS Rating Curve= 0
Exp/Cntr=.5,.3

Type RM Length L Ch R = 3 ,8075.989,,,
BEGIN DESCRIPTION:
425s1&425s2: (425s1-Lake Houston Parkway North Bound-Conc. Bridge),(425s2-Lake Houston Parkway South Bound-Concrete Bridge)
Notes: Extended bridge deck on LOB to x-sec sta 0 @ both US & DS cross section. Extended bridge deck on ROB to x-sec sta 3643.78 US and 3729.4 DS.
Used 425s2 TR elevations for upstream deck elevations & used 425s1 TR elevations for downstream deck elevations
END DESCRIPTION:
Bridge Culvert--1,0,-1,-1, 0
Deck Dist Width WeirC Skew NumUp NumDn MinLoCord MaxHiCord MaxSubmerge Is_Ogee
70.279,123,2.6,0, 12, 11, 55.94, , .95, 0, 0,0,,
       0 1471.81 1506.25    1535  1558.4 1659.91 1738.65 1785.16 1798.92 1849.19
 1885.89 3643.78
   55.94   55.94    56.3   56.52   56.74   57.22   57.17      57   56.83   56.35
   55.99   55.99
                           50.27   50.49   50.97   50.92   50.75
                
     113 1459.71 1481.86 1485.96 1523.51 1642.96 1772.27 1819.34 1823.51 1864.22
  3842.4
   56.14   56.14   56.41   56.48    56.8   57.26   56.79   56.52   56.37   55.77
   55.77
                                   50.55   51.01   50.54
        
Pier Skew, UpSta & Num, DnSta & Num=  ,1616.64, 4 ,1603.38, 4 , 3 , 3 , 0 ,,
    1.35    1.35       2       2
      37    47.8    47.8    50.8
    1.35    1.35       2       2
      37    47.8    47.8    50.8
Pier Skew, UpSta & Num, DnSta & Num=  ,1701.9, 4 ,1686.02, 4 , 3 , 3 , 0 ,,
    1.35    1.35       2       2
      37    47.8    47.8    50.8
    1.35    1.35       2       2
      37    47.8    47.8    50.8
BR Coef=-1 , 0 , 0 ,, 0 ,,,.8,-1,,0,
WSPro=,,,, 1 ,,,, 0 ,,,, 0 ,,,,-1 ,-1 ,-1 , 0 , 0 , 0 , 0 , 0
BC Design=,, 0 ,, 0 ,,,,,,

Type RM Length L Ch R = 1 ,7944.210,204.33,204.33,204.33
BEGIN DESCRIPTION:
425s1d.  Surveyed section.  XS 2/4.
Bank Station offset =      3470
Notes: Inserted Blocked Obstruction on left overbank to eliminate area from the section where flow should not be allowed to go
END DESCRIPTION:
XS GIS Cut Line= 6
     3176744.591    13947938.055     3177282.887    13946717.901
     3177563.743    13946412.409      3177731.99    13945927.428
     3177508.019    13944855.178     3177512.487    13944483.872
#Sta/Elev= 30
     113   55.25  282.64   54.83  316.22   52.34  413.54   55.21  530.36   53.24
  706.53   56.32  840.07   53.14 1042.49   56.03 1373.35   55.65 1548.82   47.21
 1575.61   39.41 1642.96    37.2 1674.59   37.43 1675.77   39.94 1712.73   38.25
 1742.69   46.08 1818.15   50.97 1987.51   53.12 2154.03   50.48 2434.26   50.55
 2587.72    53.5 2651.29   51.44 2768.68   52.29 2853.18   49.19 2978.27   51.67
 3208.16   50.83 3447.11   53.28 3647.16   48.13 3763.11    53.8  3842.4   53.82
#Mann= 3 , 0 , 0
     113     .11       0 1548.82     .04       0 1742.69     .11       0
#XS Ineff= 2 , 0
     113 1522.75   55.94 1773.72     113   55.94
Permanent Ineff=
       F       F
#Block Obstruct= 2 , 0
     113                 2587.72     113    53.5
Bank Sta=1548.82,1742.69
XS Rating Curve= 0
Exp/Cntr=.5,.3

Type RM Length L Ch R = 1 ,7739.881,1723.13,1284.39,886.36
BEGIN DESCRIPTION:
Copy of 425s1d.   XS 1/4.
Bank Station offset =      3559
Notes: Inserted Blocked Obstruction on left overbank to eliminate area from the section where flow should not be allowed to go
END DESCRIPTION:
XS GIS Cut Line= 6
      3176845.05    13947991.633     3177379.489    13946910.336
     3177660.345    13946604.844     3177828.593    13946119.862
     3177549.812    13944833.791     3177535.815    13944469.876
#Sta/Elev= 30
       0   53.97  145.94   55.09  239.52   51.96     284   54.27  429.18   52.71
  634.52   55.12  680.63   52.88  800.03   54.68  996.87   52.92 1172.93    55.5
 1347.32   47.21 1374.11   39.41 1441.46    37.2 1473.09   37.43 1474.27   39.94
 1511.23   38.25 1541.19   46.08 1565.65   49.02 1821.04   50.84 1966.93   48.46
 2211.58    51.4  2744.1   52.73 2839.34   49.62 2924.94   52.49 3178.42   50.79
 3346.64   53.31 3452.96   52.85 3608.69    48.4 3733.46   53.89 3816.76   53.86
#Mann= 4 ,-1 , 0
       0     .11       0 1347.32     .04       0 1541.19     .11       0
 1821.04     .99       0
#Block Obstruct= 2 , 0
       0                  2744.1       0      53
Bank Sta=1347.32,1541.19
XS Rating Curve= 0
Exp/Cntr=.3,.1

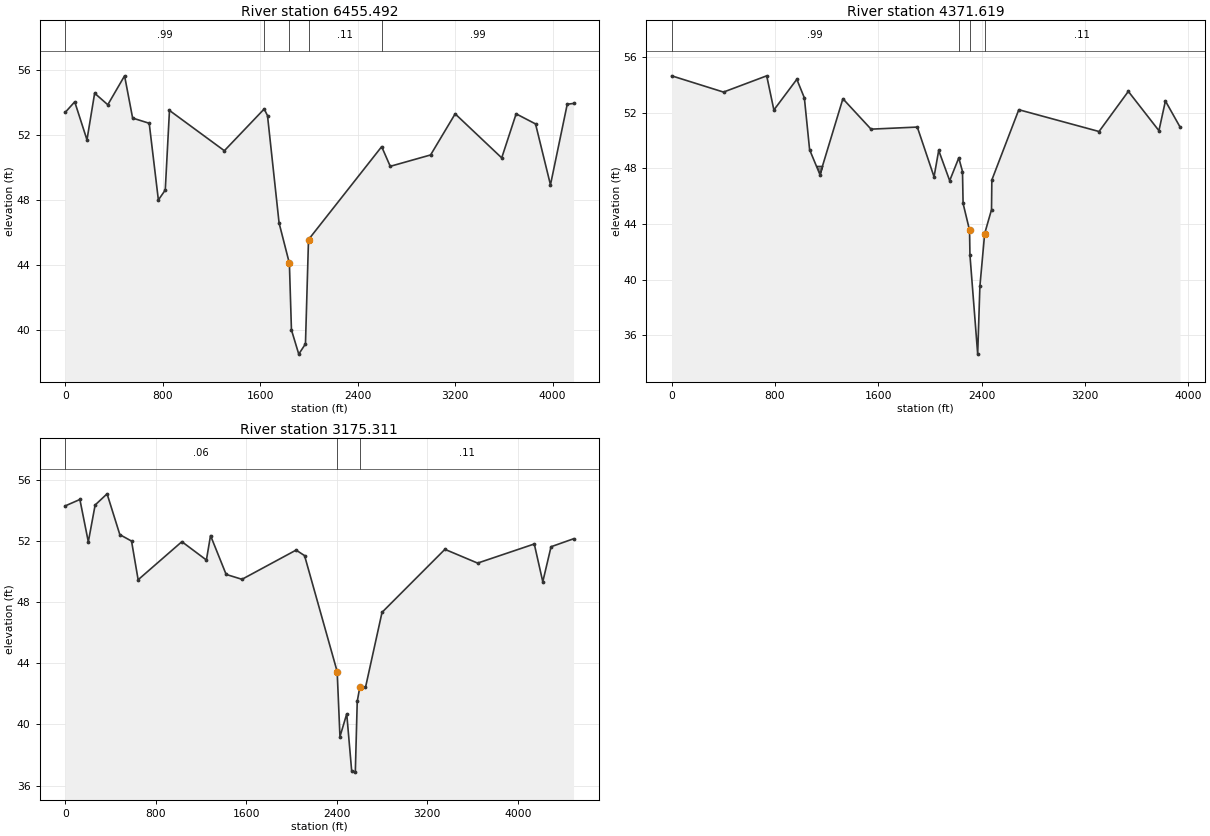
Type RM Length L Ch R = 1 ,6455.492,1750.23,2083.87,1975.16
BEGIN DESCRIPTION:
425v17
Bank Station offset =      3083
Notes: Inserted Blocked Obstruction in ROB area out of range - blocked by roadway -- LOB area is accessible to flow albeit ineffective
END DESCRIPTION:
XS GIS Cut Line= 6
     3179795.007     13947746.14     3178485.572    13946530.568
     3178231.837     13946501.45      3177670.46    13945036.532
     3177600.062    13944843.514     3177596.468    13944488.538
#Sta/Elev= 30
       0    53.4   78.11   54.05  178.58   51.71  241.57   54.58  349.49   53.87
  487.17   55.65  553.29   53.05   689.3   52.73  764.54   48.01  821.08   48.62
  855.58   53.52 1306.04   51.04 1632.87   53.61 1660.03    53.2 1755.11   46.59
 1839.56   44.11 1856.56   40.01 1916.56   38.52 1971.56   39.15 1996.56   45.57
 2596.88   51.29 2667.31   50.08 2998.38   50.78 3199.98   53.31 3581.96    50.6
 3700.31   53.31 3859.56   52.69 3982.06   48.94 4119.63    53.9 4171.33   53.95
#Mann= 5 ,-1 , 0
       0     .99       0 1632.87     .06       0 1839.56     .04       0
 1996.56     .11       0 2596.88     .99       0
#Block Obstruct= 2 , 0
       0                    3700       0   53.31
Bank Sta=1839.56,1996.56
XS Rating Curve= 0
Exp/Cntr=.3,.1

Type RM Length L Ch R = 1 ,4371.619,1178.19,1196.31,1196.31
BEGIN DESCRIPTION:
425v18
Bank Station offset =      2631
END DESCRIPTION:
XS GIS Cut Line= 6
     3180392.197    13947447.546     3180067.205    13946406.708
     3179658.576    13945320.127     3179567.065    13945112.148
     3178823.426    13944074.967     3178661.716    13943995.249
#Sta/Elev= 30
       0   54.67   401.2    53.5  735.69   54.67  791.24   52.21  968.78   54.42
  1027.2   53.08 1067.79   49.35 1147.53   47.56 1325.43   53.02 1543.29   50.83
 1901.43   50.98 2031.07    47.4 2067.11    49.3 2152.11   47.12  2222.5   48.76
 2251.27   47.78 2255.92   45.48 2305.92   43.55 2308.92   41.77 2368.92   34.63
 2385.92   39.51 2422.92   43.31 2475.92   45.03 2478.49   47.17 2687.11   52.23
 3308.26   50.66 3534.98   53.55 3771.96   50.72 3822.13   52.86 3935.01   50.99
#Mann= 4 ,-1 , 0
       0     .99       0  2222.5     .06       0 2305.92     .04       0
 2422.92     .11       0
#Block Obstruct= 1 ,-1
    1110    1190    48.2
Bank Sta=2305.92,2422.92
XS Rating Curve= 0
Exp/Cntr=.3,.1

Type RM Length L Ch R = 1 ,3175.311,3345.61,3175.31,2782.54
BEGIN DESCRIPTION:
425v19
Bank Station offset =      2436
END DESCRIPTION:
XS GIS Cut Line= 5
     3180708.888    13947357.063     3180748.388    13945008.158
     3180673.516    13944708.668     3179382.877    13943615.275
     3179253.537    13943553.732
#Sta/Elev= 30
       0   54.29  129.71   54.71  204.29   51.94  264.52   54.35  370.03   55.08
  482.84   52.41  586.27   51.99   644.6   49.46 1031.15   51.95 1247.89   50.75
 1284.44   52.35 1422.31   49.81 1562.29   49.49  2040.6    51.4 2115.45   51.04
  2403.6   43.46 2428.32    39.2  2488.2   40.69  2531.9   36.96 2564.03   36.88
 2581.03    41.5 2604.03   42.45 2654.03   42.42  2800.2   47.33 3355.83   51.45
 3644.96   50.55 4145.75    51.8 4220.95   49.33 4294.01   51.62  4492.7   52.14
#Mann= 3 , 0 , 0
       0     .06       0  2403.6     .04       0 2604.03     .11       0
Bank Sta=2403.6,2604.03
XS Rating Curve= 0
Exp/Cntr=.3,.1

Chan Stop Cuts=-1